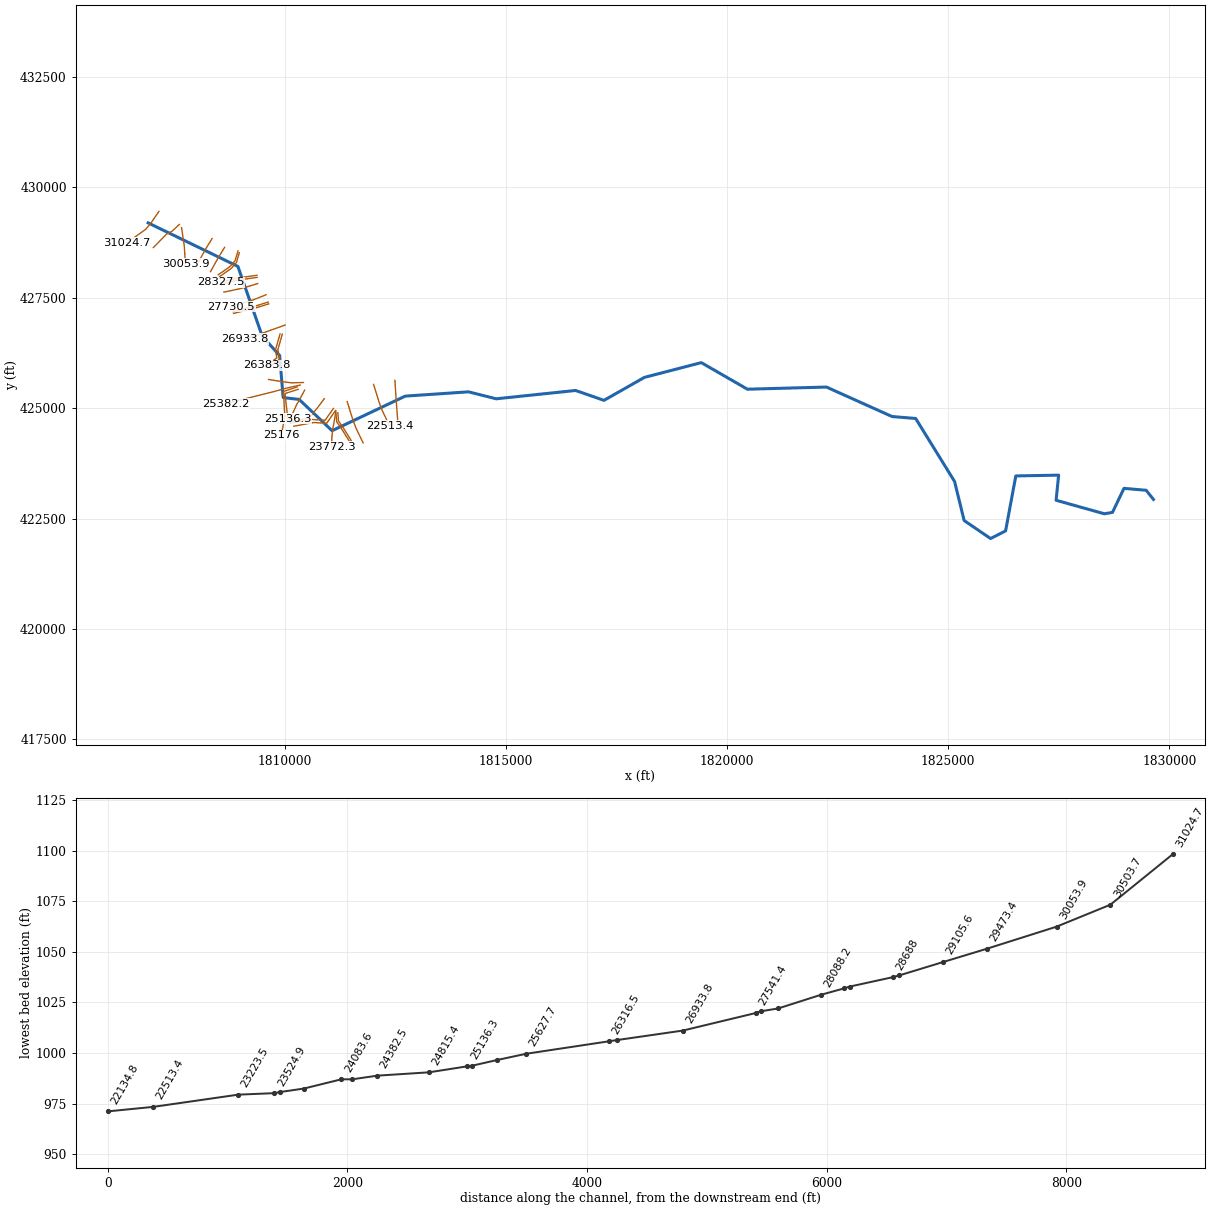
--- ScottsRun.prj (project) ---

Proj Title=ScottsRun
Current Plan=p01
Default Exp/Contr=0,0
English Units
Geom File=g01
Flow File=f01
Plan File=p01
BEGIN DESCRIPTION:
END DESCRIPTION:
DSS Export Rating Curves= 0
DSS Export Rating Curve Sorted= 0
DSS Export Volume Flow Curves= 0
DXF OffsetX= 0
DXF OffsetY= 0
DXF ScaleX= 0
DXF ScaleY= 0

--- ScottsRun.p01 (plan) ---

Plan Title=Floodplain
Program Version=4.00
Geom File=g01
Flow File=f01
K Sum by GR=0
Std Step Tol=0.01
Critical Tol=0.01
Num of Std Step Trials=20
Max Error Tol=0.3
Flow Tol Ratio=0.001
Split Flow NTrial=30
Split Flow Tol=0.02
Split Flow Ratio=0.02
Log Output Level=0
Friction Slope Method=1
Unsteady Friction Slope Method=2
Unsteady Bridges Friction Slope Method=1
Global Log Level=0
CheckData=False
Run HTab=0
Run UNet=0
Run PostProcess=0
UNET Theta=0
UNET Theta Warmup=0
UNET ZTol=0
UNET ZSATol=0
UNET MxIter=0
UNET MaxInSteps=0
UNET DtIC=0
UNET DtMin=0
UNET MaxCRTS=0
UNET WFStab=0
UNET SFStab=0
UNET WFX=0
UNET SFX=0
UNET DSS MLevel=0
UNET DZMax Abort=0
UNET Convert EG Bridges=0
UNET Use Existing IB Tables=0
UNET Froude Limit=0
UNET Froude Power=0
Write IC File=0
Echo Input=False
Echo Output=False
Write Detailed=0

--- ScottsRun.f01 (steady flow) ---

Flow Title=NFF Regression Equation
Program Version=4.10
Number of Profiles= 1
Profile Names=P100yr
River Rch & RM=ScottsRun,Main            ,31024.7
     593
River Rch & RM=ScottsRun,Main            ,28740.3
     700
River Rch & RM=ScottsRun,Main            ,28327.5
     801
River Rch & RM=ScottsRun,Main            ,25382.2
     870
River Rch & RM=ScottsRun,Main            ,24815.4
    1264
River Rch & RM=ScottsRun,Main            ,22134.8
    1356
River Rch & RM=ScottsRun,Main            ,21569.4
    1471
River Rch & RM=ScottsRun,Main            ,17196
    1638
River Rch & RM=ScottsRun,Main            ,16781.7
    1797
River Rch & RM=ScottsRun,Main            ,14975.3
    1841
River Rch & RM=ScottsRun,Main            ,14417.4
    2226
River Rch & RM=ScottsRun,Main            ,11626.9
    2291
River Rch & RM=ScottsRun,Main            ,11153.5
    2914
River Rch & RM=ScottsRun,Main            ,6895.7
    3056
River Rch & RM=ScottsRun,Main            ,6597.9
    3320
River Rch & RM=ScottsRun,Main            ,299.5
    3406
Boundary for River Rch & Prof#=ScottsRun,Main            , 1
Up Type= 0
Dn Type= 3
Dn Slope=0.00517
DSS Import GetInterval= 0
DSS Import GetPeak= 0
DSS Import FillOption= 0

--- ScottsRun.g01 (geometry) ---

Geom Title=USGS 10m DEM
Program Version=4.10

River Reach=ScottsRun       ,Main
Reach XY= 30
     1806913.507      429195.513     1808942.469      428210.659
     1809492.428      426631.177     1809886.021      426193.693
     1809965.896      425239.816     1810326.638      425198.587
      1811071.43      424490.253     1812725.063      425273.605
     1814155.654      425370.669     1814781.496       425212.94
     1816577.399      425401.553      1817217.58      425177.644
     1818132.672      425697.884     1819417.857      426031.827
     1820459.782      425430.147     1822246.755      425478.636
     1823729.844      424811.327     1824263.177      424767.056
     1825142.952      423340.841     1825359.011      422456.986
     1825956.146         422049.     1826295.729      422221.743
     1826527.066      423466.882     1827494.862      423484.244
      1827437.57      422915.667     1828527.067      422609.764
     1828711.962      422641.882     1828972.118      423184.938
     1829473.772      423141.637     1829638.554      422934.285

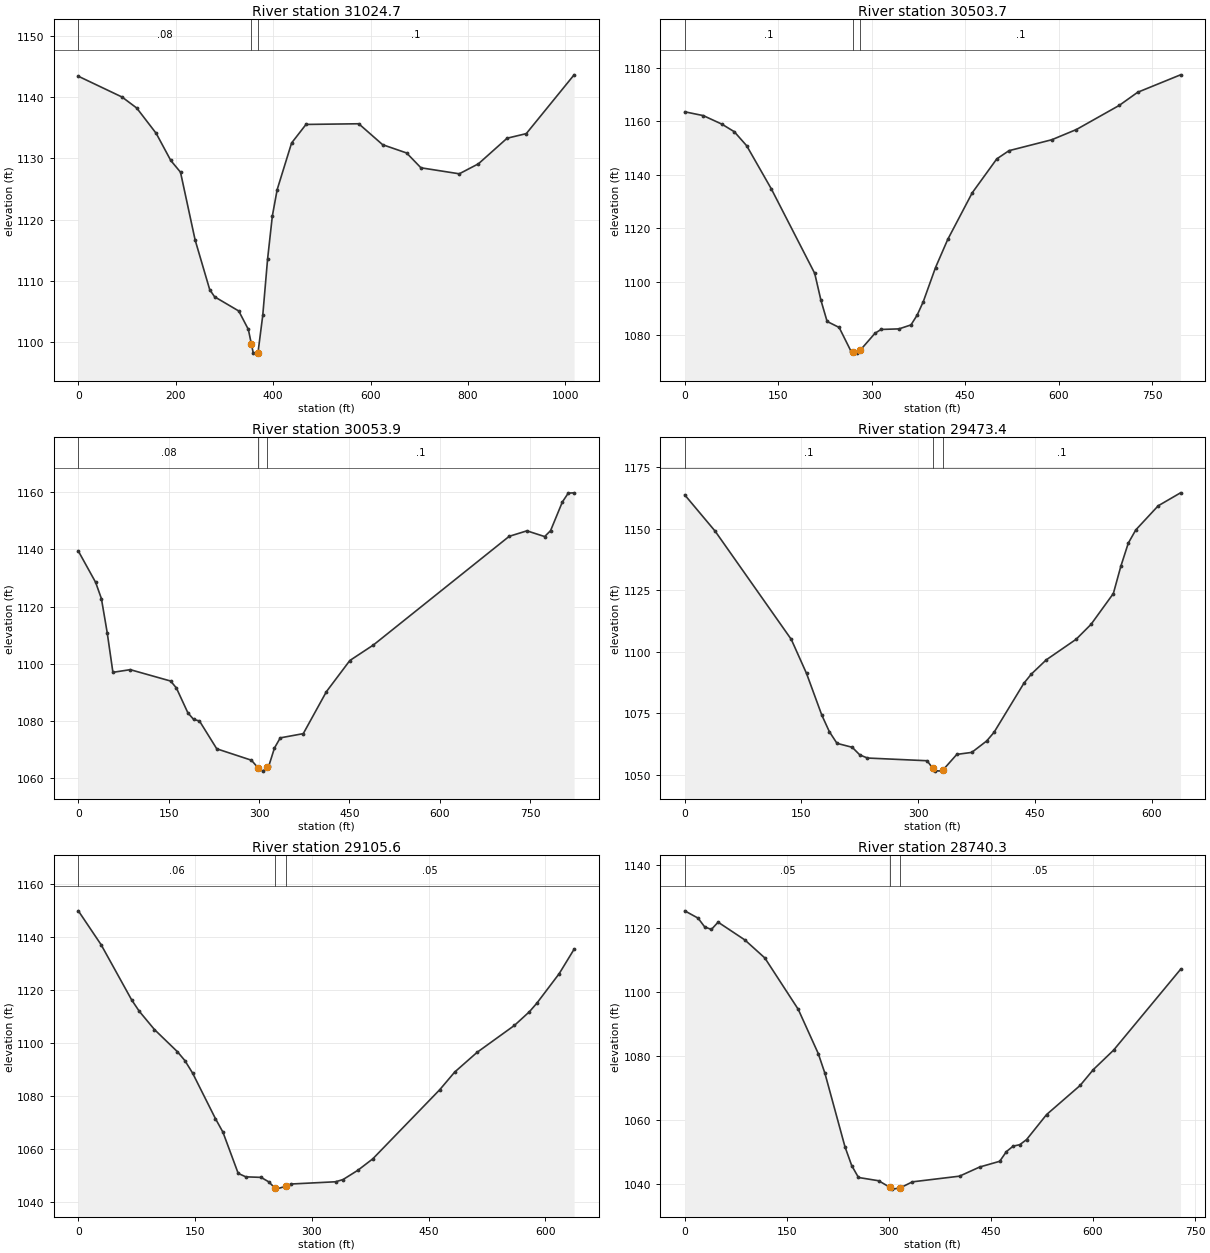
Type RM Length L Ch R = 1 ,31024.7 ,530.4,521.1,511.7
XS GIS Cut Line= 4
     1807158.144      429455.508     1806988.005      429207.244
     1806863.005      429054.466      1806441.13      428748.911
#Sta/Elev= 30
       0 1143.43    89.9 1140.03   119.9 1138.24   159.9  1134.1   189.8 1129.68
   209.8 1127.76   239.8  1116.7   269.8 1108.58   279.8 1107.42   329.4  1105.1
   349.1 1102.09  355.191099.765     359 1098.31   368.8 1098.22  368.921098.295
   378.7 1104.39   388.6 1113.57   398.4 1120.62   408.3 1124.92   437.9 1132.53
   467.5 1135.56   575.8 1135.67   624.9 1132.25   674.1  1130.9   703.5 1128.48
   782.2  1127.5   821.5 1129.13   880.4 1133.31   919.8 1134.06    1018 1143.66
#Mann= 3 , 0 , 0
       0     .08       0  355.19    .045       0  368.92      .1       0
Bank Sta=355.19,368.92
XS Rating Curve= 0 ,0
Exp/Cntr=0.3,0.1

Type RM Length L Ch R = 1 ,30503.7 ,420.8,449.8,477.2
XS GIS Cut Line= 4
     1807620.665      429161.335     1807452.696      429006.388
     1807333.013      428944.756     1807030.821      428635.294
#Sta/Elev= 30
       0 1163.55    29.8 1162.12    59.6 1158.93    79.5  1156.1    99.4 1150.85
   139.1 1134.65   208.6  1103.1   218.6 1093.02   228.5 1085.11   247.8 1082.87
     267 1073.89   270.4 1073.67   276.6 1073.26  281.941074.425   305.4  1080.7
   315.1 1082.12   343.9 1082.33   363.1 1083.82     373 1087.48   382.8 1092.49
   402.5 1105.29   422.1  1115.8   461.4 1133.24   500.8 1145.93   520.4    1149
   589.2  1153.1   628.6 1156.92   697.4 1165.95   726.9 1170.85   795.7 1177.38
#Mann= 3 , 0 , 0
       0      .1       0   270.4    .045       0  281.94      .1       0
Bank Sta=270.4,281.94
XS Rating Curve= 0 ,0
Exp/Cntr=0.3,0.1

Type RM Length L Ch R = 1 ,30053.9 ,594.5,580.6,564.8
XS GIS Cut Line= 4
     1807668.782      429089.755     1807700.032      428881.422
     1807731.282      428673.089      1807754.72      428272.047
#Sta/Elev= 30
       0 1139.43    28.7 1128.48    38.3 1122.78    47.9 1110.91    57.4 1096.98
    86.2 1097.91   153.2 1093.93   162.8  1091.5   181.9 1082.78   191.5 1080.48
   201.1 1079.95   229.8 1070.21   287.3 1066.22   298.9 1063.43   306.4  1062.4
   313.9  1063.7     316 1064.07   325.6  1070.5   335.2 1074.04   373.4 1075.52
   411.8 1090.21   450.7 1101.11   489.9 1106.56   715.3 1144.58   744.7  1146.5
   774.1 1144.49   783.9 1146.55   803.5  1156.6   813.3  1159.7     823  1159.8
#Mann= 3 , 0 , 0
       0     .08       0   298.9    .045       0   313.9      .1       0
Bank Sta=298.9,313.9
XS Rating Curve= 0 ,0
Exp/Cntr=0.3,0.1

Type RM Length L Ch R = 1 ,29473.4 ,367.8,367.8,368
XS GIS Cut Line= 4
     1808359.755      428841.925     1808231.716      428633.592
     1808147.081      428483.852     1808040.744       428290.71
#Sta/Elev= 30
       0 1163.72    39.1 1148.97   136.9 1105.02   156.5 1091.18   176.1 1074.27
   185.8 1067.55   195.6 1062.81   215.2  1061.2     225 1058.09   234.8 1056.84
   311.4 1055.74  318.751052.645     321  1051.7   330.5 1051.52     332 1052.06
   349.6 1058.32   368.8 1059.13   387.9 1063.76   397.4 1067.28   435.7 1087.19
   445.3 1090.93   464.5 1096.72   502.8 1105.06     522 1111.13   550.7 1123.66
   560.3 1134.71   569.9 1144.13   579.5 1149.49   608.3 1159.29     637 1164.56
#Mann= 3 , 0 , 0
       0      .1       0  318.75    .045       0     332      .1       0
Bank Sta=318.75,332
XS Rating Curve= 0 ,0
Exp/Cntr=0.3,0.1

Type RM Length L Ch R = 1 ,29105.6 ,370.5,365.2,358
XS GIS Cut Line= 4
     1808642.741      428642.273     1808514.703      428433.939
     1808430.067        428284.2      1808323.73      428091.057
#Sta/Elev= 30
       0 1150.01    29.3  1137.2    68.5 1116.38    78.2 1112.12    97.8 1105.18
   127.2 1096.84   136.9 1093.46   146.7 1088.79   176.1 1071.57   185.8 1066.42
   205.4 1050.86   215.2 1049.55   234.8 1049.35   244.5 1047.69   252.1 1045.49
   254.1 1044.91   267.1 1046.05   273.2 1046.84   330.5 1047.69   340.1 1048.52
   359.2 1052.04   378.3 1056.34   464.5  1082.5   483.6 1089.13   512.4 1096.58
   560.3 1106.73   579.5 1111.88   589.1 1115.12   617.8 1126.27     637 1135.52
#Mann= 3 , 0 , 0
       0     .06       0   252.1    .045       0   267.1     .05       0
Bank Sta=252.1,267.1
XS Rating Curve= 0 ,0
Exp/Cntr=0.3,0.1

Type RM Length L Ch R = 1 ,28740.3 ,51.7,52.3,51.6
XS GIS Cut Line= 4
      1808944.39      428560.241     1808877.526      428334.475
     1808758.168      428202.096     1808499.922      428021.975
#Sta/Elev= 30
       0 1125.49    19.6  1123.2    29.4 1120.43    39.2 1119.66      49 1121.94
    88.3 1116.38   117.7 1110.73   166.8 1094.64   196.2 1080.79     206 1074.61
   235.5 1051.57   245.4 1045.68   255.3 1041.97     285 1040.94  301.721038.856
   304.8 1038.32  316.081038.645   334.5  1040.6   403.8 1042.38   433.4 1045.24
   462.9 1047.04   472.7 1050.07   482.6 1051.78   492.4 1052.24   502.3 1053.83
   531.8 1061.68     581 1070.78   600.6 1075.79   630.2 1081.84   728.6 1107.15
#Mann= 3 , 0 , 0
       0     .05       0  301.72    .045       0  316.08     .05       0
Bank Sta=301.72,316.08
XS Rating Curve= 0 ,0
Exp/Cntr=0.3,0.1

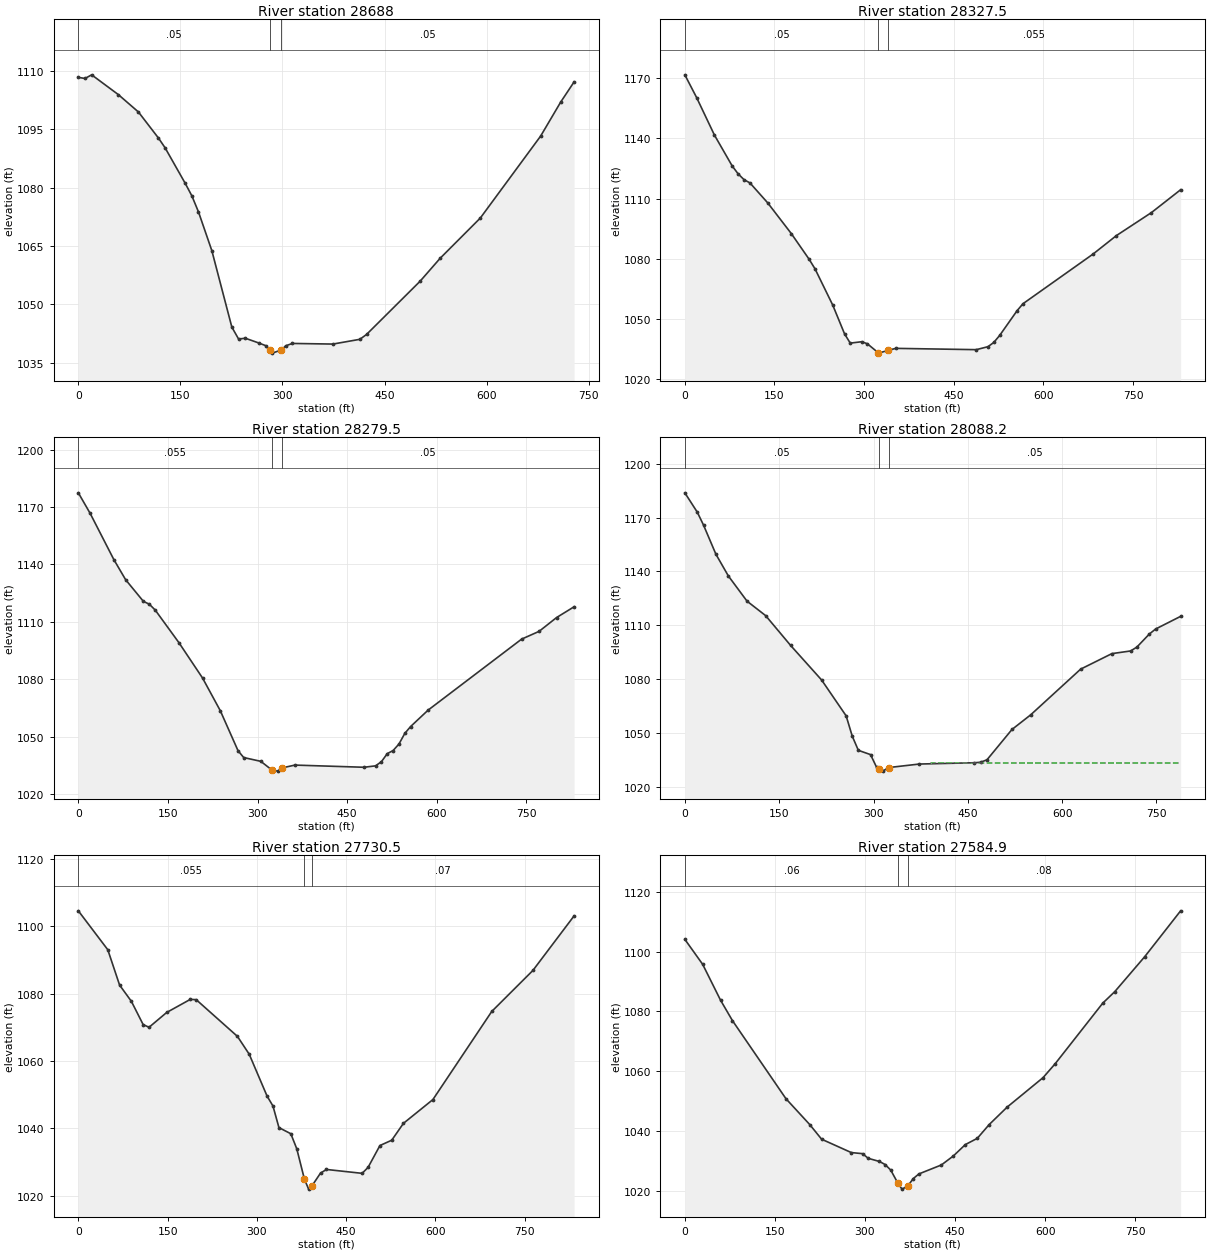
Type RM Length L Ch R = 1 ,28688   ,375.9,360.5,344.7
XS GIS Cut Line= 4
     1808974.772      428519.009     1808907.908      428293.242
      1808788.55      428160.863     1808530.304      427980.742
#Sta/Elev= 30
       0 1108.37     9.8 1108.08    19.6 1109.02    58.9 1103.92    88.3 1099.47
   117.7 1092.78   127.5 1090.26     157 1081.15   166.8 1077.92   176.6 1073.77
   196.2 1063.82   225.6 1044.16   235.5  1041.1   245.4  1041.3   265.2 1040.08
   275.1 1039.41   281.3  1038.2     285 1037.47  298.361038.284   304.8 1039.36
   314.7 1039.96   374.1  1039.8   413.7 1041.02   423.5 1042.26   502.3 1055.96
   531.8 1061.87   590.8 1072.21   679.4 1093.27   708.9 1102.02   728.6 1107.21
#Mann= 3 , 0 , 0
       0     .05       0   281.3    .045       0  298.36     .05       0
Bank Sta=281.3,298.36
XS Rating Curve= 0 ,0
Exp/Cntr=0.3,0.1

Type RM Length L Ch R = 1 ,28327.5 ,48.2,48,48.2
XS GIS Cut Line= 4
     1809371.907      428009.026     1809107.151      427972.134
      1808946.56      427952.602     1808560.276      427846.266
#Sta/Elev= 30
       0 1171.78    19.8 1160.36    49.5  1141.7    79.2 1126.29    89.1 1122.35
      99 1119.44   108.9 1117.82   138.6 1107.87   178.2 1092.49   207.9 1079.72
   217.8 1074.92   247.5  1056.8   267.3 1042.41   276.8 1037.81   295.9  1038.5
   305.4 1037.49  323.261033.094   324.4 1032.81   339.4 1034.13     353 1035.19
   487.7 1034.54   507.3 1036.03     517 1038.14   526.8 1041.62   556.1 1054.04
   565.9 1057.49   683.2 1082.29   722.2  1091.5   780.9    1103   829.7  1114.4
#Mann= 3 , 0 , 0
       0     .05       0  323.26    .045       0   339.4    .055       0
Bank Sta=323.26,339.4
XS Rating Curve= 0 ,0
Exp/Cntr=0.3,0.1

Type RM Length L Ch R = 1 ,28279.5 ,187.8,191.3,194.4
XS GIS Cut Line= 4
     1809376.248      427961.283     1809111.491      427924.391
     1808950.901      427904.859     1808564.616      427798.523
#Sta/Elev= 30
       0 1177.43    19.8 1166.68    59.4 1142.54    79.2 1131.98   108.9 1120.67
   118.8  1119.2   128.7 1116.12   168.3  1099.1   207.9 1080.58   237.6 1063.49
   267.3 1042.56   276.8    1039   305.4 1037.02   324.4 1032.38   333.9  1031.9
   340.2 1033.54   362.5 1035.06     478 1033.92   497.5 1034.66   507.3 1036.86
     517 1041.04   526.8 1042.67   536.6 1046.08   546.4 1051.65   556.1 1055.22
   585.4 1063.81   741.8 1100.92   771.1 1104.99   800.4 1112.22   829.7 1117.85
#Mann= 3 , 0 , 0
       0    .055       0   324.4    .045       0   340.2     .05       0
Bank Sta=324.4,340.2
XS Rating Curve= 0 ,0
Exp/Cntr=0.3,0.1

Type RM Length L Ch R = 1 ,28088.2 ,355.4,357.7,358.6
XS GIS Cut Line= 4
     1809390.956      427821.275     1809173.123      427755.988
     1808967.345      427699.747     1808627.067      427628.566
#Sta/Elev= 30
       0 1183.82    19.8 1173.03    29.7 1165.84    49.4 1149.61    69.2  1137.5
    98.9 1123.46   128.5  1115.4   168.1 1098.84   217.5 1079.54   256.5 1059.56
   266.2 1048.26   275.9 1040.36   295.3 1037.97     305 1030.84   309.2 1029.94
   314.7 1028.77   324.2 1030.76   372.9 1032.72   460.6 1033.44   470.5 1033.73
   480.5  1035.1   520.2 1051.98     550 1060.14   629.4 1085.59   679.1 1094.24
   708.9 1095.72   718.8 1097.87   738.7 1105.17   748.6 1107.94   788.4    1115
#Mann= 3 , 0 , 0
       0     .05       0   309.2    .045       0   324.2     .05       0
#XS Ineff= 2 , 0
                          392.16         1033.05
Permanent Ineff=
       F       F
Bank Sta=309.2,324.2
XS Rating Curve= 0 ,0
Exp/Cntr=0.3,0.1

Type RM Length L Ch R = 1 ,27730.5 ,146.9,145.6,144.3
XS GIS Cut Line= 4
     1809581.928      427569.539     1809315.484      427462.585
     1809106.234      427395.927      1808795.47      427296.969
#Sta/Elev= 30
       0 1104.54    49.5    1093    69.3 1082.53    89.1 1077.71   108.9 1070.81
   118.8 1070.01   148.5 1074.41   188.1 1078.28     198  1078.2   267.3 1067.31
   287.1 1062.02   317.1  1049.6     327 1046.66     337 1040.27     357 1038.44
     367 1033.97  379.881024.937   386.9 1022.02   392.2 1022.91   406.9 1026.78
   416.9 1027.85   476.8  1026.7   486.8 1028.48   506.7 1034.95   526.5 1036.52
   546.2 1041.53   595.7 1048.58   694.5 1074.69   763.7 1086.87   832.9 1103.05
#Mann= 3 , 0 , 0
       0    .055       0  379.88    .045       0   392.2     .07       0
Bank Sta=379.88,392.2
XS Rating Curve= 0 ,0
Exp/Cntr=0.3,0.1

Type RM Length L Ch R = 1 ,27584.9 ,43.6,43.5,43.6
XS GIS Cut Line= 4
     1809627.984      427403.557     1809363.227      427321.092
     1809217.828        427284.2     1808831.543      427186.543
#Sta/Elev= 30
       0  1104.1    29.7 1095.75    59.4 1083.79    79.2 1076.96   168.4 1050.83
     208 1042.19   227.8 1037.29   277.3 1032.82     296 1032.46   305.4  1030.9
   324.2 1029.84   333.6 1028.82   342.9 1026.98   355.1  1022.5   361.7  1020.6
   371.1 1021.59   380.4 1024.11   389.8 1025.68   427.3 1028.68   447.2 1031.68
   467.2 1035.49   487.1 1037.58     507  1042.2   536.9 1048.03   596.6 1057.86
   616.6 1062.46   696.2  1082.8   716.2 1086.64     766 1098.31   825.8 1113.64
#Mann= 3 , 0 , 0
       0     .06       0   355.1    .045       0   371.1     .08       0
Bank Sta=355.1,371.1
XS Rating Curve= 0 ,0
Exp/Cntr=0.3,0.1

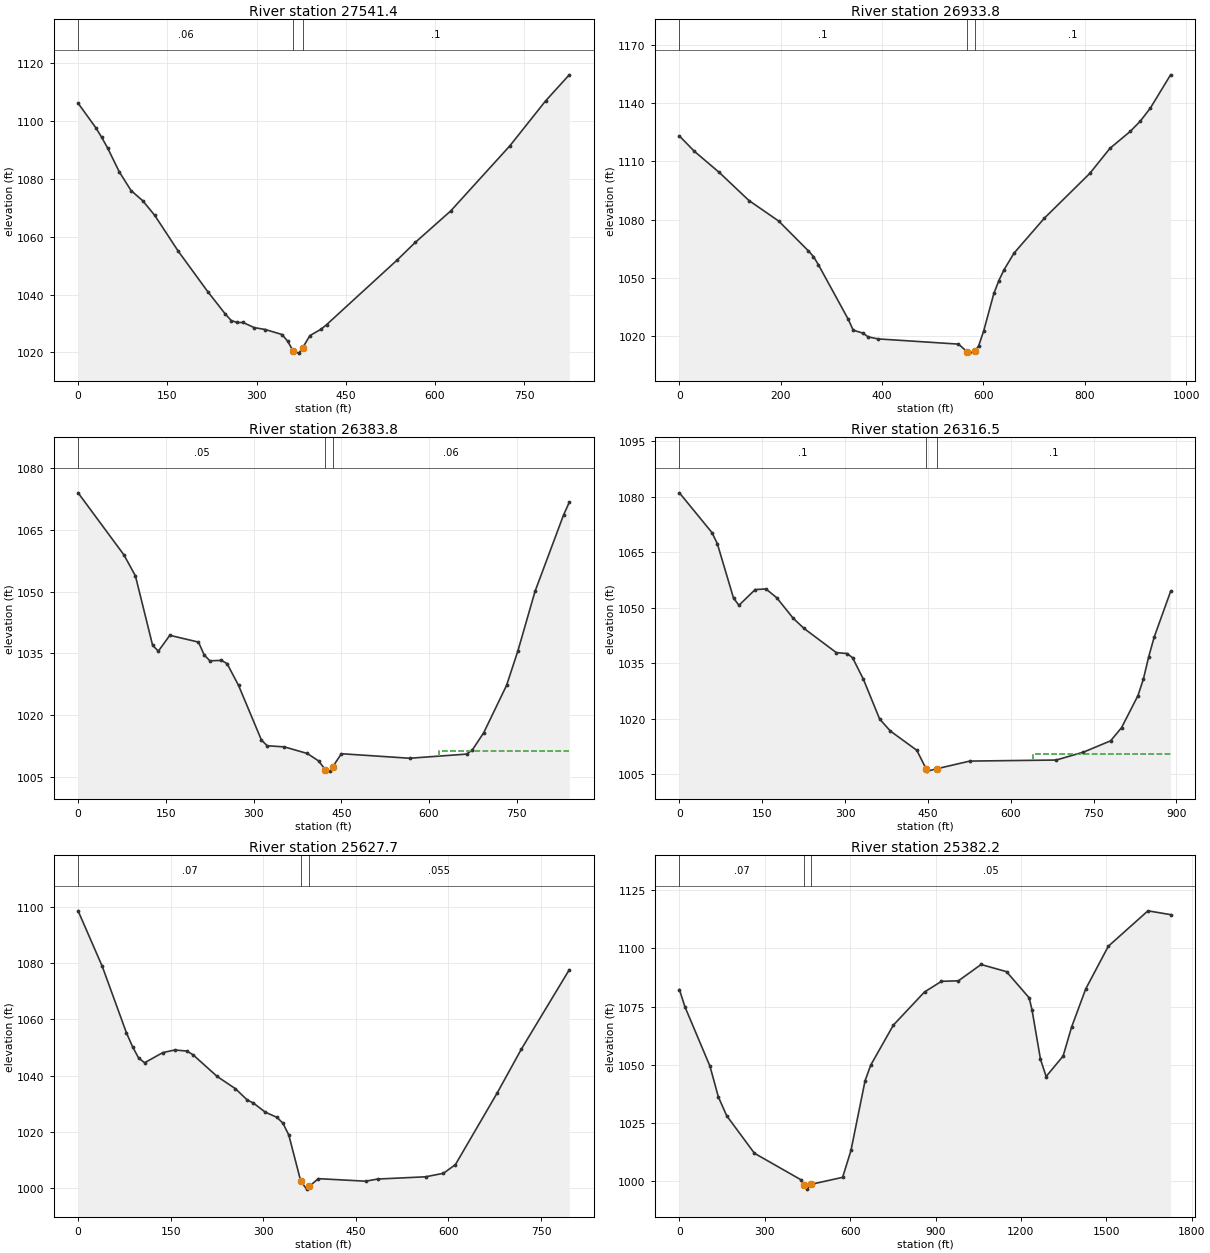
Type RM Length L Ch R = 1 ,27541.4 ,604.5,607.6,608.8
XS GIS Cut Line= 4
     1809641.005      427362.325     1809376.248      427279.859
     1809230.848      427242.967     1808844.564      427145.311
#Sta/Elev= 30
       0 1106.23    29.7 1097.75    39.6 1094.44    49.5 1090.77    69.3 1082.44
    89.1 1075.98   108.9 1072.43   128.8 1067.42   168.4    1055   217.9 1041.04
   247.6 1033.24   257.5 1031.01   267.4 1030.33   277.3 1030.34     296 1028.57
   314.8  1027.9   342.9 1026.17   352.3 1023.88   361.7 1020.42   371.1 1019.73
   377.3  1021.5   389.8  1025.8   408.6 1028.02   417.9  1029.6   536.9 1052.04
   566.8 1058.03   626.5 1068.94   726.1 1091.51   785.9 1106.99   825.8 1116.04
#Mann= 3 , 0 , 0
       0     .06       0   361.7    .045       0   377.3      .1       0
Bank Sta=361.7,377.3
XS Rating Curve= 0 ,0
Exp/Cntr=0.3,0.1

Type RM Length L Ch R = 1 ,26933.8 ,515.5,549.9,582.1
XS GIS Cut Line= 4
     1810009.928      426882.724     1809604.112      426737.325
     1809369.737      426652.689      1809094.13      426565.884
#Sta/Elev= 30
       0 1123.11    29.4 1115.24    78.4 1104.36   137.2 1089.82   195.9 1079.23
   254.7 1063.79   264.5 1060.92   274.3 1056.67   333.1 1028.57   342.9 1022.92
   362.5 1021.37   372.3 1019.47   391.9 1018.42   550.7 1015.73   567.5 1011.84
   570.6 1011.08   582.5 1011.94   590.6  1014.9   600.5 1022.61   620.5 1041.89
   630.4 1048.54   640.4 1054.02   660.3 1062.68   720.1  1080.7   809.8  1103.8
   849.6 1116.76   889.5 1125.45   909.4 1130.75   929.4 1137.56   969.2 1154.67
#Mann= 3 , 0 , 0
       0      .1       0   567.5    .045       0   582.5      .1       0
Bank Sta=567.5,582.5
XS Rating Curve= 0 ,0
Exp/Cntr=0.3,0.1

Type RM Length L Ch R = 1 ,26383.8 ,66.5,67.3,160.7
XS GIS Cut Line= 4
     1809894.911      426678.731     1809792.914      426320.658
     1809822.404      426138.294      1809596.71      425968.155
#Sta/Elev= 30
       0 1074.03    78.4 1058.94      98 1053.84   127.4 1036.97   137.2 1035.55
   156.8  1039.4   205.8 1037.75   215.6 1034.62   225.4  1033.2     245 1033.31
   254.7 1032.52   274.3 1027.23   313.5 1013.92   323.3 1012.56   352.7 1012.28
   391.8 1010.68   411.2 1008.87   422.7 1006.74   430.6 1006.39  435.62  1007.5
   450.1 1010.62   566.8 1009.52   664.3 1010.53     674 1011.54   693.5 1015.73
   732.5 1027.23     752 1035.66   781.2 1050.08   829.9 1068.62   839.7 1071.72
#Mann= 3 , 0 , 0
       0     .05       0   422.7    .045       0  435.62     .06       0
#XS Ineff= 2 , 0
                          617.32         1011.22
Permanent Ineff=
       F       F
Bank Sta=422.7,435.62
XS Rating Curve= 0 ,0
Exp/Cntr=0.3,0.1

Type RM Length L Ch R = 1 ,26316.5 ,733.9,688.9,550.7
XS GIS Cut Line= 4
     1809946.994      426678.731     1809844.998      426320.658
      1809889.16      426114.278     1809648.275      425925.476
#Sta/Elev= 30
       0  1081.1    58.8 1070.36    68.6 1067.36      98  1052.6   107.8 1050.66
   137.2 1054.92   156.8 1055.08   176.4 1052.68   205.8 1047.19   225.4 1044.43
   284.1 1037.86   303.7  1037.6   313.5 1036.48   333.1 1030.67   362.5  1019.9
   381.9 1016.64   429.9 1011.42  446.99 1006.32   449.1 1005.78   466.9 1006.45
   525.8  1008.5   682.1 1008.78   731.5 1010.91   780.8 1013.98   800.6 1017.54
   830.2 1026.18   840.1 1030.66   849.9  1036.8   859.8 1042.08   889.4 1054.41
#Mann= 3 , 0 , 0
       0      .1       0  446.99    .045       0   466.9      .1       0
#XS Ineff= 2 , 0
                          641.11         1010.42
Permanent Ineff=
       F       F
Bank Sta=446.99,466.9
XS Rating Curve= 0 ,0
Exp/Cntr=0.3,0.1

Type RM Length L Ch R = 1 ,25627.7 ,236.1,245.4,254.2
XS GIS Cut Line= 4
     1810425.184      425581.726     1810150.879      425574.781
     1809951.226      425599.087     1809635.254       425651.17
#Sta/Elev= 30
       0 1098.55    39.2 1078.78    78.4 1055.15    88.2 1050.28      98 1046.25
   107.8 1044.56   137.2 1048.16   156.8  1049.1   176.4  1048.7   186.2  1047.4
   225.4 1039.67   254.8 1035.35   274.4 1031.26     284 1030.25   303.1 1027.02
   322.3 1025.14   331.9 1023.07   341.4 1018.86   360.6  1002.6   370.2  999.64
   374.8  1000.7   389.3 1003.36   465.9 1002.46   485.2 1003.22   562.9 1004.02
     592 1005.27   611.4 1008.37   679.3 1033.92   718.1 1049.36   795.8  1077.6
#Mann= 3 , 0 , 0
       0     .07       0   360.6    .045       0   374.8    .055       0
Bank Sta=360.6,374.8
XS Rating Curve= 0 ,0
Exp/Cntr=0.3,0.1

Type RM Length L Ch R = 1 ,25382.2 ,140.8,206.2,237.3
XS GIS Cut Line= 4
     1810350.966      425523.566     1810055.393      425458.462
     1809775.801      425380.901     1808676.842      425104.859
#Sta/Elev= 30
       0 1082.27    19.5 1074.83   107.4 1049.33   136.7 1036.19     166 1028.09
   263.6 1011.94   428.4 1000.45   438.1  998.25   447.7  996.53  461.49998.5583
   573.5  1001.6   602.8 1013.15   652.4 1043.11   672.3 1049.83   751.8 1067.01
   861.2 1081.24   920.8 1085.82   980.4 1086.04    1060 1093.05  1149.4 1089.97
  1228.9 1078.73  1238.9 1073.63  1268.7 1052.36  1288.6 1044.92  1348.2 1053.69
    1378 1066.13  1427.7 1082.55  1507.2  1100.9  1646.4 1116.11  1725.9 1114.48
#Mann= 3 , 0 , 0
       0     .07       0   438.1    .045       0  461.49     .05       0
Bank Sta=438.1,461.49
XS Rating Curve= 0 ,0
Exp/Cntr=0.3,0.1

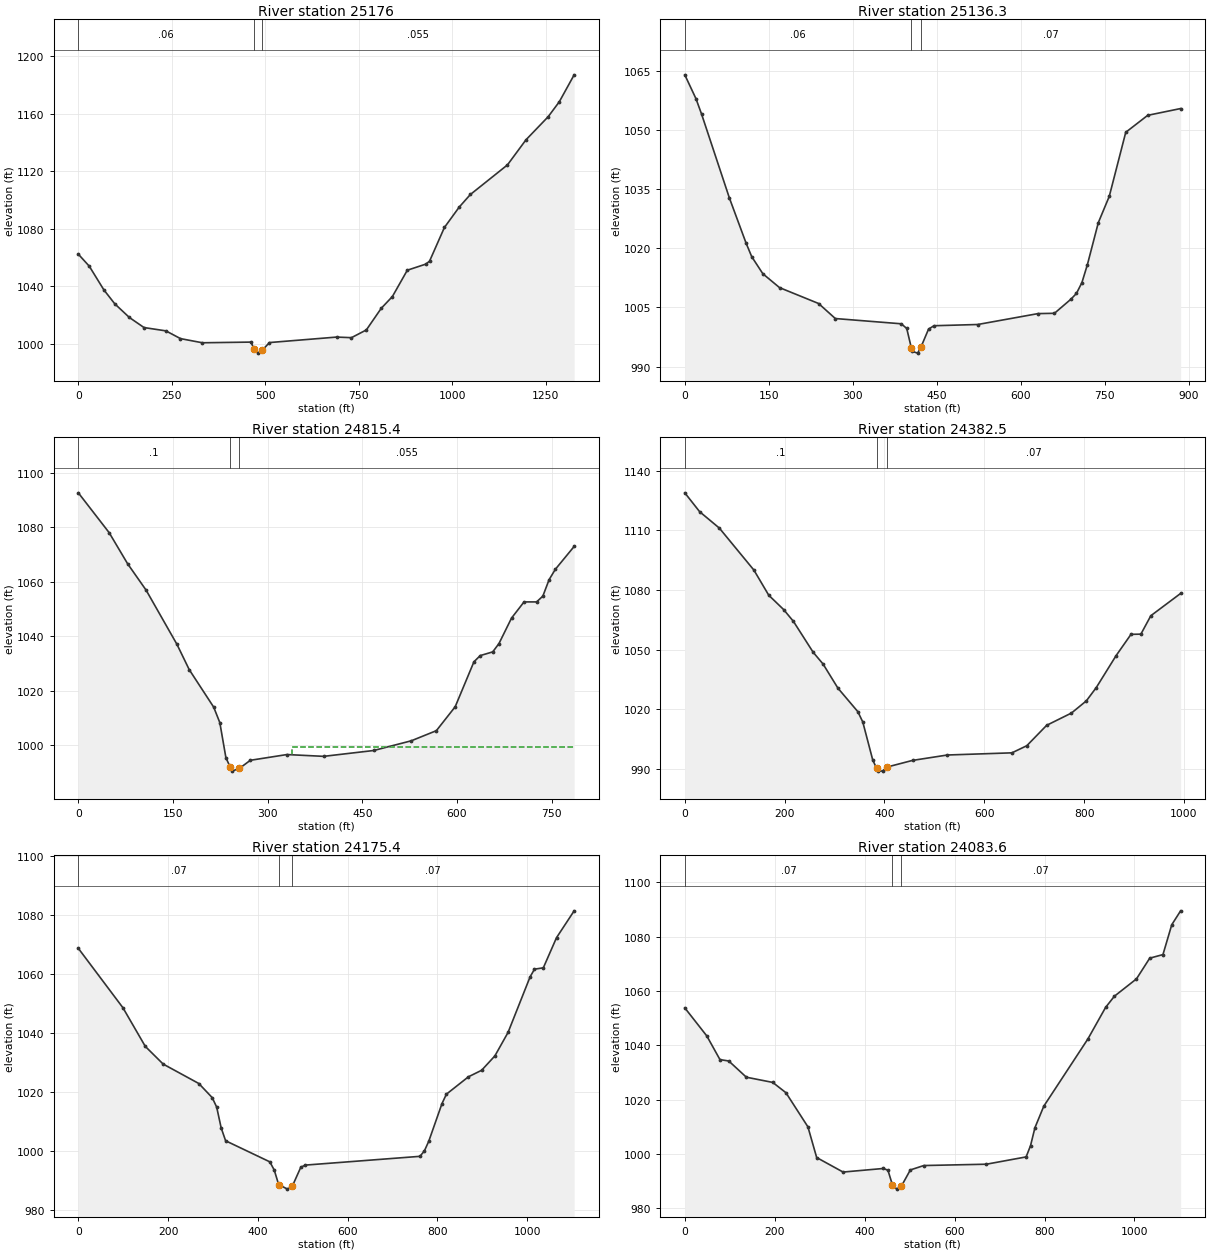
Type RM Length L Ch R = 1 ,25176   ,71.1,39.7,40.4
XS GIS Cut Line= 5
     1810284.559      425482.767     1809970.323      425376.865
     1809986.391      425128.167     1810002.363      424800.172
     1809924.238      424391.318
#Sta/Elev= 30
       0 1062.42    29.3 1054.06    68.3 1037.63    97.5 1027.94   136.5 1018.47
   175.6 1011.49   234.1 1009.19   273.1 1003.81   331.6 1000.93   461.2  1001.4
   469.8  996.77   481.1  993.74   491.1  995.63     511 1001.08   690.3 1004.88
   730.1 1004.47   769.9 1009.84   809.7 1024.85   839.5 1033.01   879.4 1051.29
     929 1055.54   938.9  1057.6   978.6 1080.97  1018.2 1095.13    1048 1103.85
  1147.1 1124.39  1196.6  1141.8  1256.1 1157.88  1285.8 1168.26  1325.4 1186.91
#Mann= 3 , 0 , 0
       0     .06       0   469.8    .045       0   491.1    .055       0
Bank Sta=469.8,491.1
XS Rating Curve= 0 ,0
Exp/Cntr=0.3,0.1

Type RM Length L Ch R = 1 ,25136.3 ,334.6,320.9,307.2
XS GIS Cut Line= 4
     1810303.006       425425.91      1810008.96       425332.16
      1810029.36      425128.601     1810072.242      424758.939
#Sta/Elev= 30
       0 1063.93    19.9  1057.9    29.9 1054.01    79.6 1032.75   109.5 1021.28
   119.5 1017.87   139.4 1013.54   169.2 1010.03   238.9 1006.01   268.8  1002.2
   386.6 1000.87   396.3  999.69   404.4  994.85     406  993.89   415.8  993.44
  422.14995.1132   435.3  999.53     445 1000.38     523 1000.69   630.7 1003.45
   660.1 1003.53   689.5  1007.1   699.3 1008.55   709.1 1011.29   718.9 1015.84
   738.4 1026.48     758 1033.16   787.4 1049.37   826.6 1053.67   885.4 1055.39
#Mann= 3 , 0 , 0
       0     .06       0   404.4    .045       0  422.14     .07       0
Bank Sta=404.4,422.14
XS Rating Curve= 0 ,0
Exp/Cntr=0.3,0.1

Type RM Length L Ch R = 1 ,24815.4 ,438.3,432.9,427.5
XS GIS Cut Line= 4
     1810452.016      425407.811       1810358.7       425236.37
     1810269.724       425075.78     1810098.283      424706.856
#Sta/Elev= 30
       0 1092.55    48.8 1077.95    78.1 1066.53   107.4 1056.85   156.2    1037
   175.7  1027.7   214.5 1013.93   224.2 1008.25   233.8  995.42   240.3   992.1
   243.5  990.47   255.3  991.48   272.5  994.44   330.5  996.55   388.7  995.89
   468.1  998.04   527.6  1001.6   567.3 1005.31   597.1 1014.08   626.8 1030.57
   636.8 1032.85   656.6 1034.21   666.5 1037.28   686.4 1046.62   706.2 1052.54
   726.1 1052.54     736 1054.66   745.9  1060.7   755.8  1064.5   785.6 1072.89
#Mann= 3 , 0 , 0
       0      .1       0   240.3    .045       0   255.3    .055       0
#XS Ineff= 2 , 0
                          337.86          999.47
Permanent Ineff=
       F       F
Bank Sta=240.3,255.3
XS Rating Curve= 0 ,0
Exp/Cntr=0.3,0.1

Type RM Length L Ch R = 1 ,24382.5 ,231.7,207.1,182
XS GIS Cut Line= 4
     1810894.724      425214.668     1810723.283      424984.634
     1810545.332      424782.811     1810119.985      424680.814
#Sta/Elev= 30
       0 1128.94    29.7 1119.45    69.2 1111.19   138.5 1090.02   168.2 1077.38
   197.9 1070.19   217.6 1064.23   257.2 1048.65     277 1042.75   306.8 1030.59
   346.7 1018.75   356.6 1013.55   376.6  994.36  384.48990.1363   386.6     989
   396.5  988.81   404.2   990.8   456.3  994.21   526.1  996.93   655.4  998.02
   685.2  1001.6     725 1011.88   774.7 1018.06   804.5 1024.18   824.4 1030.88
   864.1 1046.96     894 1057.69   913.8 1057.79   933.7 1067.06   993.4 1078.28
#Mann= 3 , 0 , 0
       0      .1       0  384.48    .045       0   404.2     .07       0
Bank Sta=384.48,404.2
XS Rating Curve= 0 ,0
Exp/Cntr=0.3,0.1

Type RM Length L Ch R = 1 ,24175.4 ,92.9,91.8,91.6
XS GIS Cut Line= 4
     1811103.058      424993.314     1810912.085      424726.387
     1810597.415      424745.918     1810143.856      424661.283
#Sta/Elev= 30
       0 1068.73    99.5 1048.54   149.2 1035.46     189 1029.46   268.5 1022.86
   298.4 1018.06   308.3 1014.84   318.3  1007.8   328.2 1003.43   426.7  996.28
   436.6  993.48   446.4  988.57   466.1  987.02   477.1   988.1   495.7  994.43
   505.6  995.17   761.3  998.15   771.1  999.98   780.9 1003.27   810.4 1016.06
   820.2 1019.24   869.3 1025.14   898.7 1027.35   928.2 1032.22   957.6  1040.2
  1006.7 1059.05  1016.5 1061.66  1036.2 1062.12  1065.6 1072.35  1104.9 1081.46
#Mann= 3 , 0 , 0
       0     .07       0   446.4    .045       0   477.1     .07       0
Bank Sta=446.4,477.1
XS Rating Curve= 0 ,0
Exp/Cntr=0.3,0.1

Type RM Length L Ch R = 1 ,24083.6 ,271.8,311.3,350.4
XS GIS Cut Line= 4
     1811148.576      424946.888     1810948.978      424656.943
     1810660.349      424676.474      1810206.79      424591.839
#Sta/Elev= 30
       0 1053.78    48.9 1043.45    78.2 1034.72    97.8 1034.21   136.9 1028.24
   195.6 1026.32   224.9 1022.53   273.8 1009.96   293.3  998.64     352   993.3
   441.8  994.62   451.8  993.96   461.7  988.61   471.7  987.01   481.7  988.11
   501.6  994.08   531.6   995.7   670.7  996.19   759.1  998.88   768.9 1003.02
   778.7 1009.64   798.4 1017.57   896.5 1042.34   935.8 1053.94   955.4 1058.07
  1004.5 1064.46    1034 1072.09  1063.4 1073.41    1083 1084.41  1102.7 1089.53
#Mann= 3 , 0 , 0
       0     .07       0   461.7    .045       0   481.7     .07       0
Bank Sta=461.7,481.7
XS Rating Curve= 0 ,0
Exp/Cntr=0.3,0.1

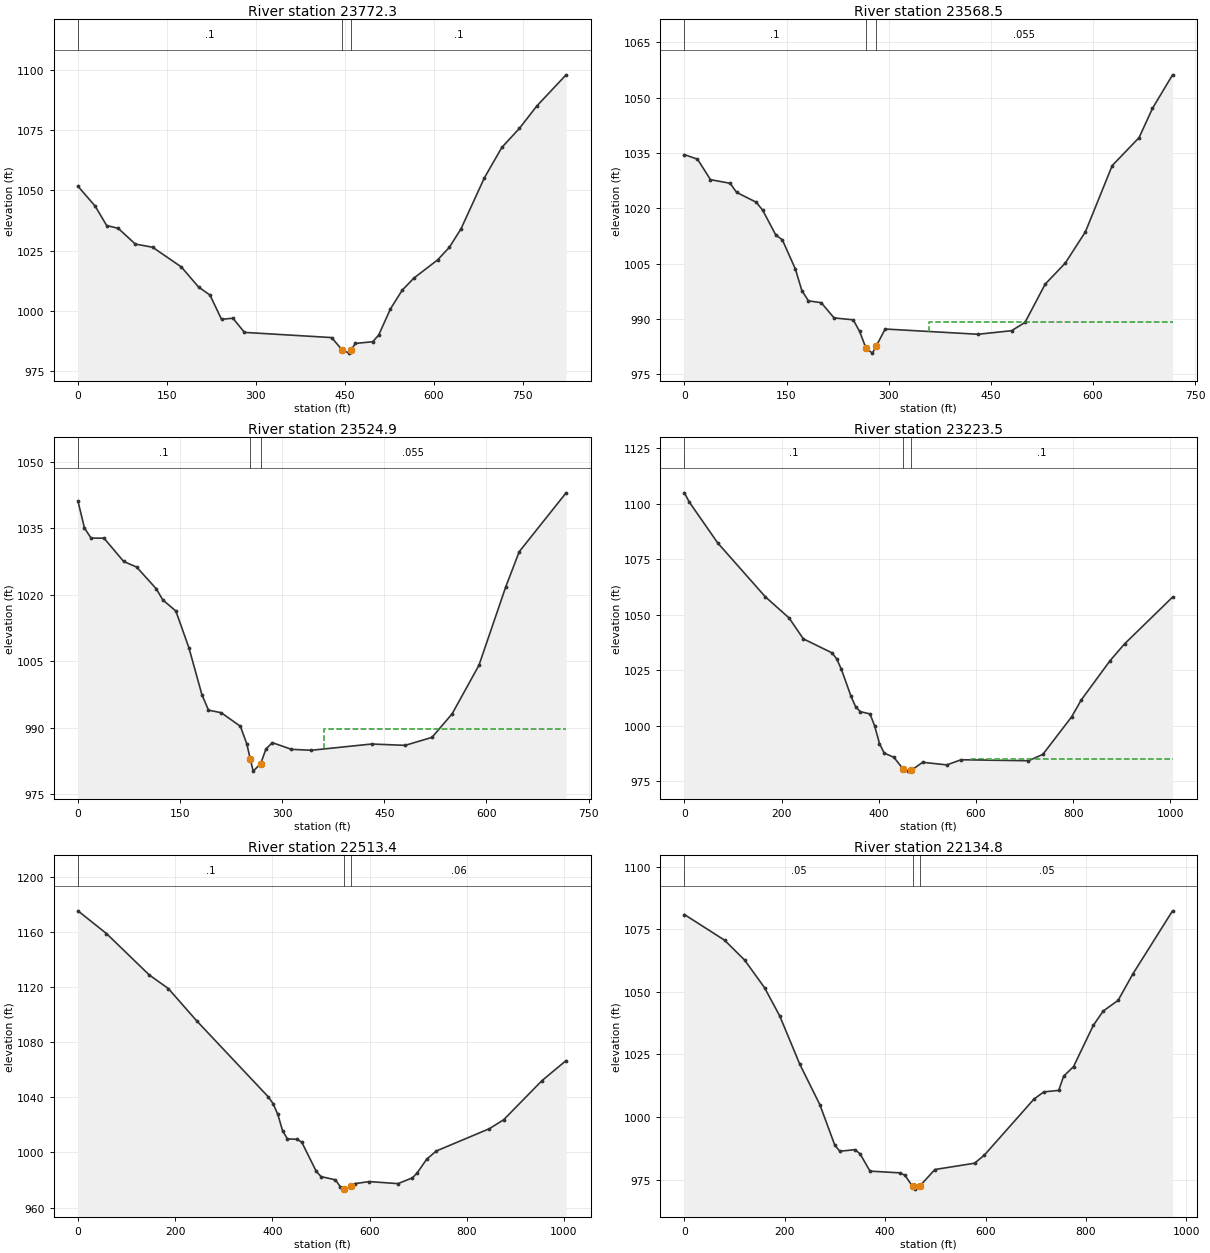
Type RM Length L Ch R = 1 ,23772.3 ,186.6,203.9,221.1
XS GIS Cut Line= 5
     1811158.342      424936.037     1811111.738      424659.113
     1811090.826      424553.914     1811064.784      424327.134
     1811063.699       424120.32
#Sta/Elev= 30
       0 1051.75      29 1043.51    48.4 1035.45    67.8 1034.29    96.8 1027.74
   125.9 1026.43   174.3 1018.26   203.4 1009.92   222.7 1006.56   242.1  996.51
   261.4  996.96   280.8  991.08   427.8  988.93   445.4  983.83   457.6  982.47
   460.4   983.6   467.5  986.47   497.2  987.22   507.2  990.01     527 1000.84
   546.9 1008.64   566.7 1013.65   606.4 1021.15   626.2 1026.36   645.9 1034.04
   685.3 1055.19   714.8 1067.85   744.4 1075.75   773.9 1085.09   823.2    1098
#Mann= 3 , 0 , 0
       0      .1       0   445.4    .045       0   460.4      .1       0
Bank Sta=445.4,460.4
XS Rating Curve= 0 ,0
Exp/Cntr=0.3,0.1

Type RM Length L Ch R = 1 ,23568.5 ,43.6,43.6,43.6
XS GIS Cut Line= 4
     1811160.078      424880.047     1811176.354      424689.075
     1811254.533      424583.592     1811463.463      424249.622
#Sta/Elev= 30
       0 1034.55    19.2 1033.31    38.3 1027.76    67.1 1026.77    76.7  1024.3
   105.4 1021.64     115 1019.46   134.2 1012.74   143.8 1011.44   162.9 1003.53
   172.5  997.65   182.1  994.88     201  994.37   219.8  990.24   247.9  989.73
   257.3  986.58   266.7     982   276.1  980.69   281.7  982.59   294.8  987.23
   431.3  985.81   480.5  986.78   500.2  989.02   529.8   999.4   559.3 1005.12
   588.9 1013.59   628.3 1031.59   667.7 1039.16   687.4  1047.1   716.9  1056.2
#Mann= 3 , 0 , 0
       0      .1       0   266.7    .045       0   281.7    .055       0
#XS Ineff= 2 , 0
                          359.87          989.24
Permanent Ineff=
       F       F
Bank Sta=266.7,281.7
XS Rating Curve= 0 ,0
Exp/Cntr=0.3,0.1

Type RM Length L Ch R = 1 ,23524.9 ,307.6,301.3,295
XS GIS Cut Line= 4
     1811201.745      424896.975     1811218.021      424706.002
       1811296.2      424600.519      1811505.13      424266.549
#Sta/Elev= 30
       0 1041.14     9.6 1035.06    19.2  1032.8    38.3 1032.77    67.1 1027.52
    86.2 1026.25     115 1021.35   124.6 1018.84   143.8 1016.33   162.9 1008.06
   182.1  997.42   191.7  993.95   210.4  993.37   238.6   990.3   247.9  986.36
   253.3  982.81   257.3  980.18   268.3  981.84   276.1  985.17   285.4  986.61
   313.6   985.1   342.7  984.89   431.3   986.3   480.5     986   519.9   987.8
   549.5  993.11   588.9 1004.08   628.3 1021.79     648 1029.71   716.9 1043.01
#Mann= 3 , 0 , 0
       0      .1       0   253.3    .045       0   268.3    .055       0
#XS Ineff= 2 , 0
                           361.2          989.61
Permanent Ineff=
       F       F
Bank Sta=253.3,268.3
XS Rating Curve= 0 ,0
Exp/Cntr=0.3,0.1

Type RM Length L Ch R = 1 ,23223.5 ,710.4,710.1,709.8
XS GIS Cut Line= 4
     1811413.388      425149.564     1811534.915      424756.769
     1811610.747      424552.734     1811773.631      424214.234
#Sta/Elev= 30
       0 1104.92     9.8 1100.83    68.5 1082.34   166.4 1058.06   215.4  1048.5
   244.7 1039.09   303.5 1032.79   313.3 1030.08   323.1 1025.31   342.6 1013.33
   352.4  1008.4   362.2 1006.24   381.8 1005.25   391.6  999.79   401.4  991.86
   411.2  987.55     431  985.69   450.7   980.2   460.6  979.44   466.8  979.79
   490.3  983.43   539.8  982.25   569.5  984.57   707.9  984.12   737.6     987
   796.9 1003.95   816.7 1011.57     876 1029.28   905.6 1036.79  1004.5  1057.9
#Mann= 3 , 0 , 0
       0      .1       0   450.7    .045       0   466.8      .1       0
#XS Ineff= 2 , 0
                          589.13          984.73
Permanent Ineff=
       F       F
Bank Sta=450.7,466.8
XS Rating Curve= 0 ,0
Exp/Cntr=0.3,0.1

Type RM Length L Ch R = 1 ,22513.4 ,385.1,378.6,372.2
XS GIS Cut Line= 4
     1812010.176      425538.019     1812131.703      425145.224
     1812207.535      424941.189     1812370.419      424602.689
#Sta/Elev= 30
       0 1175.33    58.7 1158.84   146.8 1128.79     186 1118.95   244.7 1095.37
   391.6 1040.39   401.4 1035.51   411.2  1027.7   421.1 1015.77     431 1009.89
   450.7 1009.56   460.6 1007.43   490.3  986.36   500.2   982.5   529.9  980.13
   539.8  975.14   547.9  973.72   549.7   973.4   562.9  975.65   569.5  977.36
   599.2  978.88   658.5  977.39   688.2  981.59     698  985.11   717.8   995.2
   737.6  1001.1   846.3  1017.2     876 1023.74   955.1 1052.21  1004.5 1066.67
#Mann= 3 , 0 , 0
       0      .1       0   547.9    .045       0   562.9     .06       0
Bank Sta=547.9,562.9
XS Rating Curve= 0 ,0
Exp/Cntr=0.3,0.1

Type RM Length L Ch R = 1 ,22134.8 ,60.6,60.5,60.4
XS GIS Cut Line= 3
     1812492.381      425630.033     1812521.317      425171.366
     1812559.655      424659.981
#Sta/Elev= 30
       0 1080.91    79.9 1070.66   119.9 1062.72   159.8 1051.61   189.8 1040.41
   229.8 1021.09   269.8 1004.93   299.7  988.68   309.7  986.33   339.7  986.94
   349.7  985.34   369.7  978.37   429.6  977.68   439.6  976.64   454.6  972.24
   459.6  971.18   469.6  972.58     499  979.02   577.9  981.53   597.6  984.79
   696.3 1007.16     716 1010.04   745.6 1010.63   755.4 1016.32   775.2 1020.15
   814.6 1036.65   834.3 1042.35   863.9  1046.6   893.5 1057.23   972.4 1082.38
#Mann= 3 , 0 , 0
       0     .05       0   454.6    .045       0   469.6     .05       0
#XS Ineff= 2 , 0
          409.52  977.75
Permanent Ineff=
       F       F
Bank Sta=454.6,469.6
XS Rating Curve= 0 ,0
Exp/Cntr=0.3,0.1