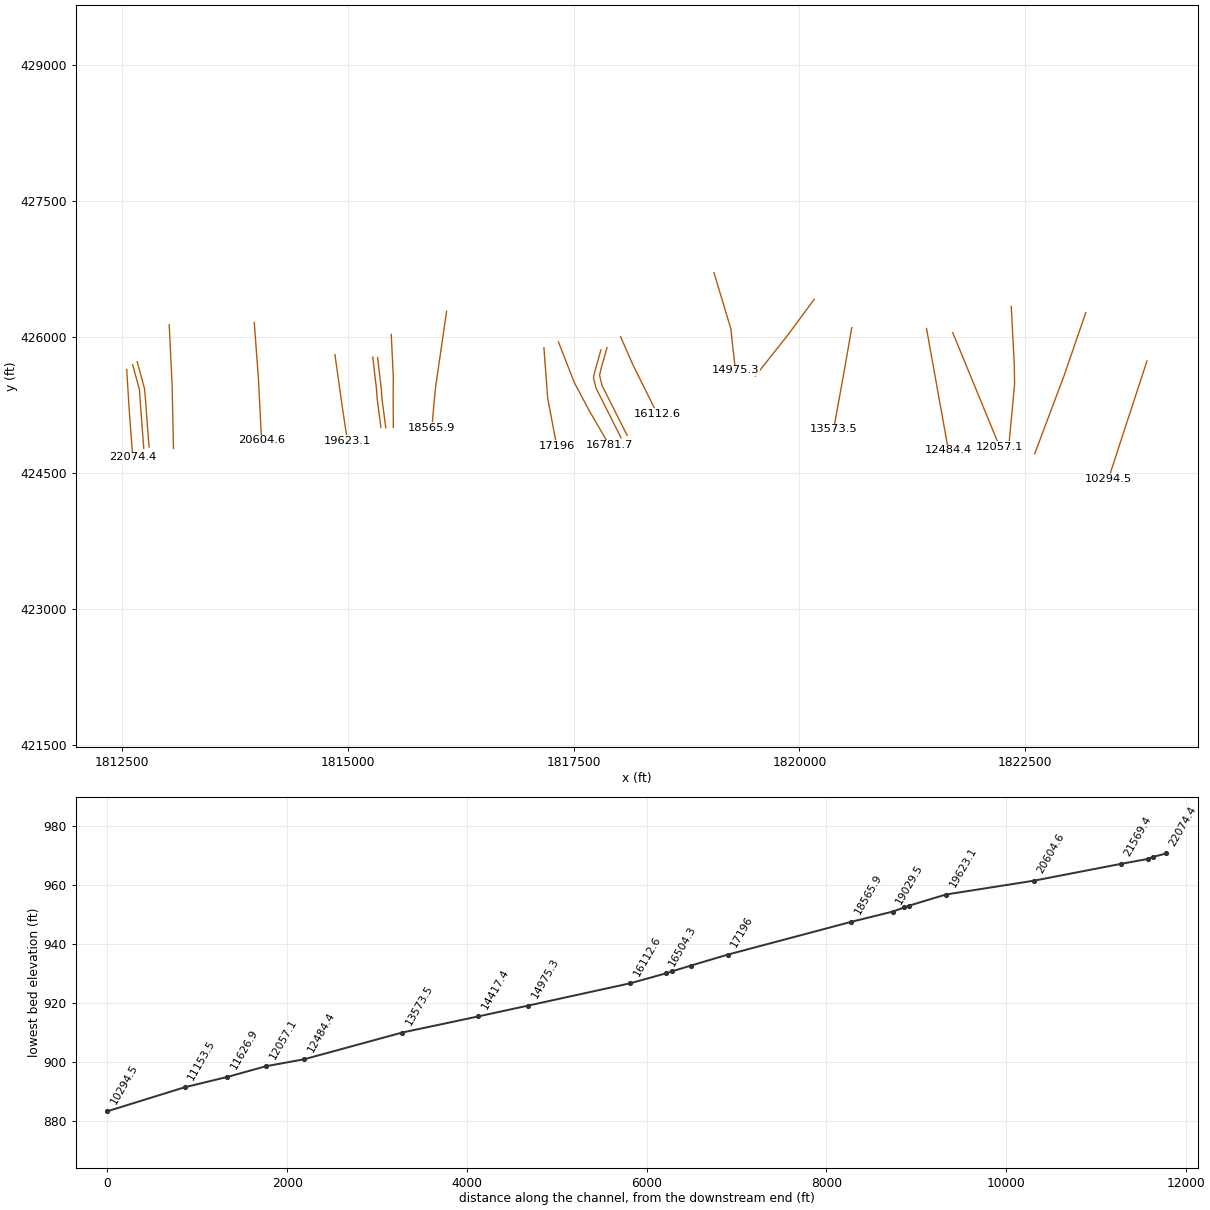
HEC-RAS study ScottsRun.prj: ScottsRun

--- ScottsRun.g01 (geometry) --- (continued)

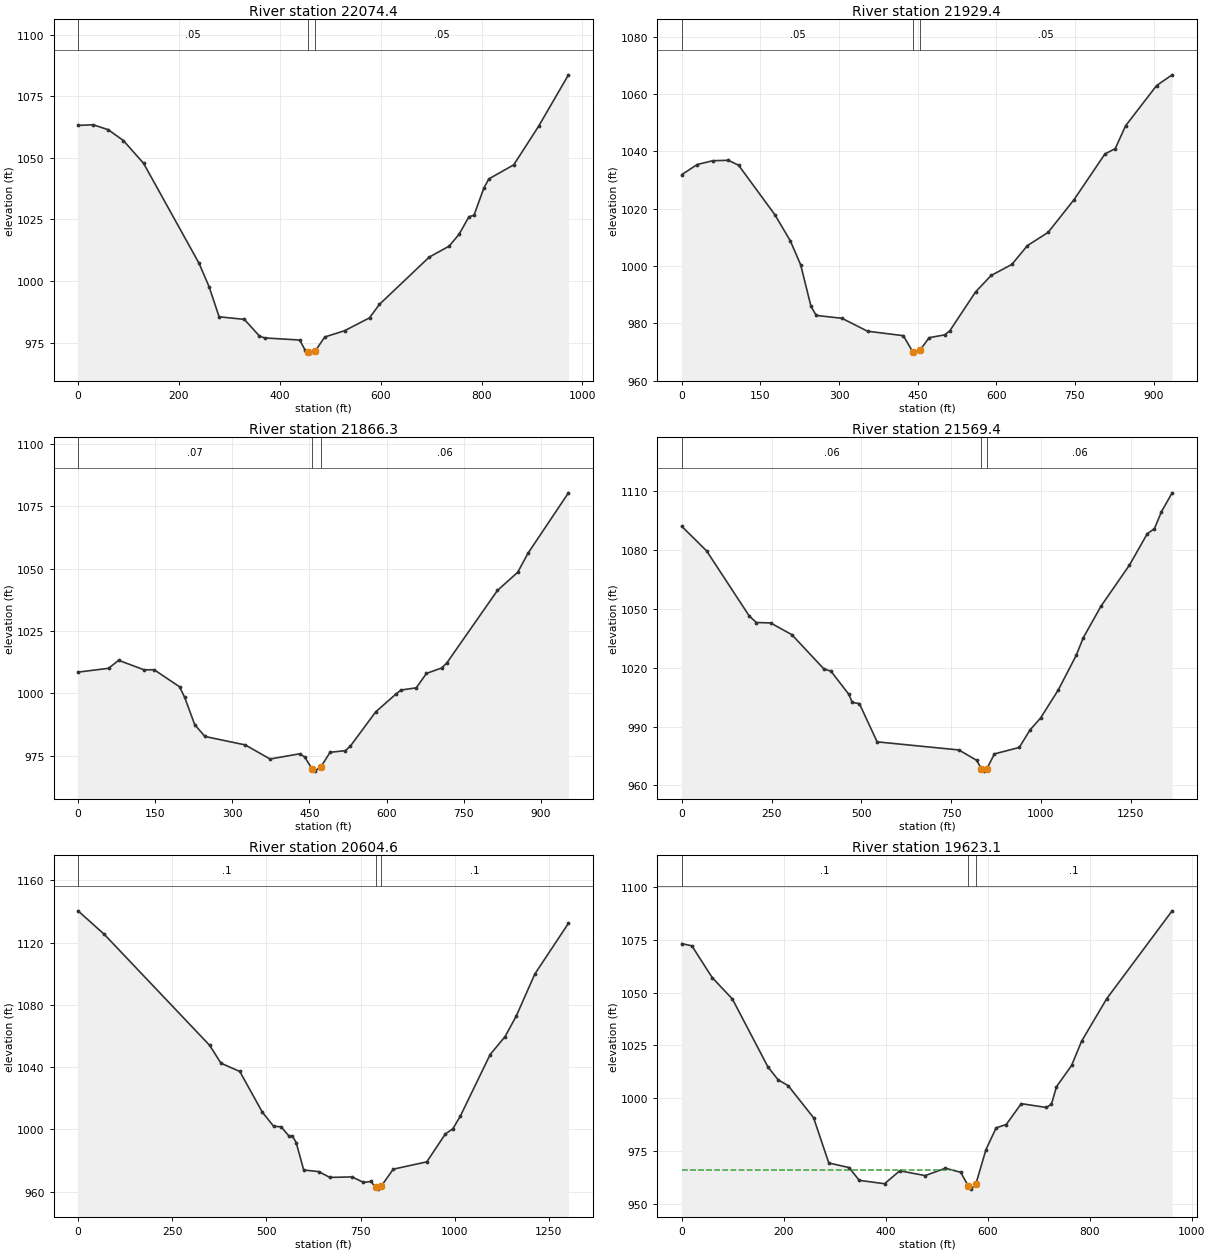
Type RM Length L Ch R = 1 ,22074.4 ,145.8,145,143.9
XS GIS Cut Line= 3
     1812550.974      425645.224     1812579.911      425186.556
     1812618.249      424675.172
#Sta/Elev= 30
       0 1063.18      30 1063.43      60 1061.42    89.9 1057.03   129.9 1047.81
   239.8 1007.26   259.8  997.74   279.7  985.52   329.7  984.48   359.7  977.71
   369.7  976.95   439.6   976.1   449.6   972.2   455.2   971.4   459.6  970.78
   470.2   971.6   489.2  977.33   528.6  979.88   577.9   985.1   597.6  990.56
   696.3 1009.74   735.7 1014.18   755.4 1018.96   775.2 1026.16     785 1026.68
   804.8 1037.83   814.6 1041.48   863.9 1047.18   913.2 1062.83   972.4  1083.7
#Mann= 3 , 0 , 0
       0     .05       0   455.2    .045       0   470.2     .05       0
Bank Sta=455.2,470.2
XS Rating Curve= 0 ,0
Exp/Cntr=0.3,0.1

Type RM Length L Ch R = 1 ,21929.4 ,62.2,63,63.9
XS GIS Cut Line= 4
     1812616.531      425698.407      1812692.84      425422.685
     1812701.439      425286.383     1812739.776      424774.998
#Sta/Elev= 30
       0 1031.88    29.6 1035.41    59.2 1036.73    88.8 1036.88   108.5 1035.16
   177.6 1017.91   207.2 1008.76   226.9 1000.42   246.6   985.9   256.5  982.76
   305.6  981.76   354.4  977.25   422.7  975.69  441.38969.8719   442.4   969.6
  454.72970.6864     472  974.99   501.6  975.97   511.4  977.39   560.7     991
   590.3   996.7   629.8 1000.55   659.4 1007.11   698.8 1011.71   748.1 1023.08
   807.3 1039.08     827 1040.96   846.7 1048.91   905.9 1062.96   935.5  1066.7
#Mann= 3 , 0 , 0
       0     .05       0  441.38    .045       0  454.72     .05       0
Bank Sta=441.38,454.72
XS Rating Curve= 0 ,0
Exp/Cntr=0.3,0.1

Type RM Length L Ch R = 1 ,21866.3 ,298.1,296.9,295.7
XS GIS Cut Line= 4
     1812667.529      425730.959     1812747.824       425435.82
     1812760.033      425301.574      1812798.37      424790.189
#Sta/Elev= 30
       0 1008.54    59.2 1010.06    78.9 1013.27   128.3 1009.46     148 1009.48
   197.3 1002.67   207.2  998.47   226.9  987.47   246.7  982.77   325.1  979.37
   373.3  973.74     431  975.82   440.7  974.53  455.02  969.77   460.4  968.88
  472.14970.5995     490  976.42   519.6  977.08   529.4  978.87   578.7  992.61
   618.2  999.78     628 1001.36   657.6 1002.25   677.4 1008.01   706.9  1010.2
   716.8 1012.16   815.4 1041.24   854.9 1048.54   874.6 1056.07   953.5 1080.35
#Mann= 3 , 0 , 0
       0     .07       0  455.02    .045       0  472.14     .06       0
Bank Sta=455.02,472.14
XS Rating Curve= 0 ,0
Exp/Cntr=0.3,0.1

Type RM Length L Ch R = 1 ,21569.4 ,964.2,964.8,965.5
XS GIS Cut Line= 3
     1813021.895      426138.172     1813054.597      425456.509
     1813068.943      424773.859
#Sta/Elev= 30
       0 1092.15    69.2 1079.62   187.9 1046.41   207.7 1043.06   247.3 1042.85
   306.6 1036.85   395.6 1019.41   415.4 1018.22   464.9 1006.49   474.8 1002.29
   494.5  1001.7     544  982.17   771.5  978.03     821  972.76   834.2  968.46
   840.8  967.23   849.2  968.36   870.5  976.02   939.7  979.31   969.4   988.2
   999.1  994.36  1048.6 1008.76  1098.1 1026.27  1117.9 1035.31  1167.3 1051.43
  1246.5 1072.39    1296 1088.36  1315.8  1090.9  1335.6 1099.61  1365.2 1109.23
#Mann= 3 , 0 , 0
       0     .06       0   834.2    .045       0   849.2     .06       0
Bank Sta=834.2,849.2
XS Rating Curve= 0 ,0
Exp/Cntr=0.3,0.1

Type RM Length L Ch R = 1 ,20604.6 ,980.4,981.5,982.3
XS GIS Cut Line= 3
     1813963.753      426163.034      1814009.44      425545.759
     1814044.216      424863.845
#Sta/Elev= 30
       0 1140.45    69.9 1125.26   349.4 1053.96   379.4 1042.48   429.3  1037.2
   489.2 1011.01   519.1 1001.97   539.1 1001.59   559.1   995.9     569  995.66
     579   991.5     599  973.85   638.8   972.8   668.4  969.08   727.8  969.39
   757.5  965.85   777.3  966.45   789.7   962.8   797.1  961.54   804.7   963.4
   836.7  974.37   925.7  979.07   975.2  997.04     995 1000.36  1014.8 1008.49
    1094 1048.08  1133.5 1059.61  1163.2 1072.79  1212.7 1099.91  1301.8 1132.44
#Mann= 3 , 0 , 0
       0      .1       0   789.7    .045       0   804.7      .1       0
Bank Sta=789.7,804.7
XS Rating Curve= 0 ,0
Exp/Cntr=0.3,0.1

Type RM Length L Ch R = 1 ,19623.1 ,409.7,407.8,406
XS GIS Cut Line= 3
     1814856.528      425809.619     1814942.877      425199.114
     1814995.003      424857.912
#Sta/Elev= 30
       0 1073.22    19.9 1072.15    59.7 1057.14    99.4 1046.93   169.1 1014.75
     189 1008.67   208.8 1005.88   258.6  990.66   288.4  969.24   328.2  967.06
   348.1     961   397.8   959.4   427.6  965.53   477.4  963.25   517.1  966.75
     547  964.82   561.8  958.38   566.9  956.84   576.8  959.25   596.7  975.62
   616.6  985.88   636.3  987.47   665.9  997.35   715.2  995.54   725.1  997.13
   734.9 1005.38   764.5 1015.44   784.2 1026.97   833.5 1047.13   961.7 1088.75
#Mann= 3 , 0 , 0
       0      .1       0   561.8    .045       0   576.8      .1       0
#XS Ineff= 2 , 0
          536.27  965.71
Permanent Ineff=
       F       F
Bank Sta=561.8,576.8
XS Rating Curve= 0 ,0
Exp/Cntr=0.3,0.1

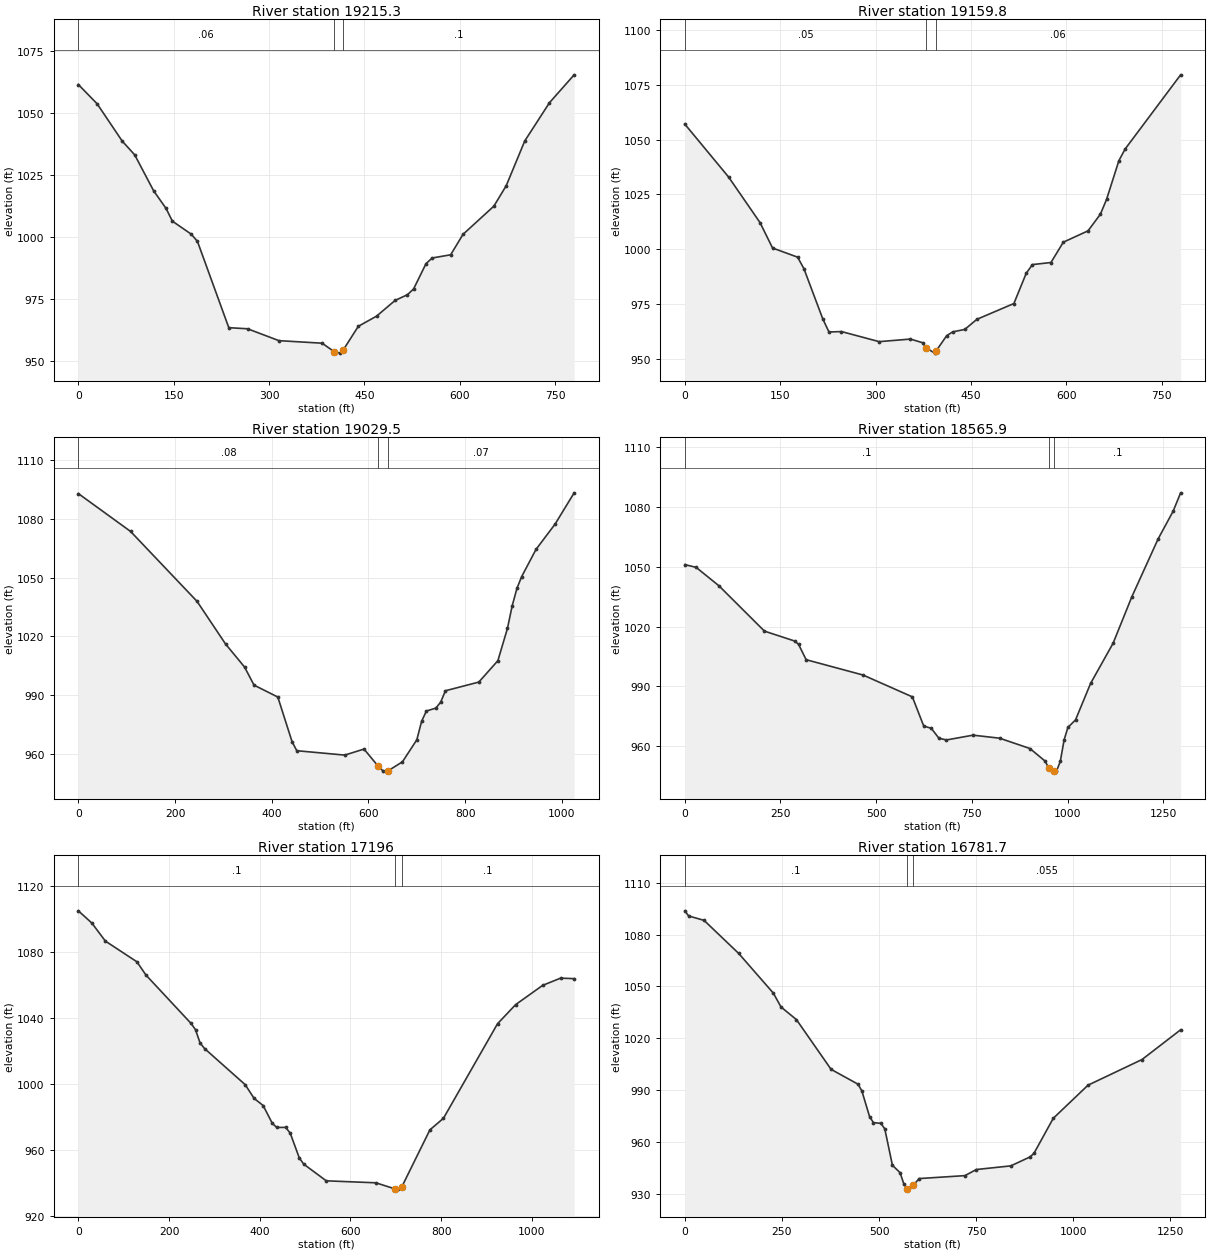
Type RM Length L Ch R = 1 ,19215.3 ,55.5,55.5,55.6
XS GIS Cut Line= 4
     1815275.385      425781.089     1815317.051      425428.659
     1815323.996      425324.492     1815365.663      425006.784
#Sta/Elev= 30
       0 1061.56    29.6 1053.76      69 1038.71    88.7 1033.13   118.3 1018.69
     138 1011.49   147.9 1006.38   177.4 1001.15   187.3  998.22   236.6  963.36
   266.2  962.91   315.4  958.12   383.4  957.09   402.3  953.67   411.8  953.08
   416.5  954.33   440.3  963.91     469  968.02   498.1  974.36   517.5  976.67
   527.2  978.99   546.7   989.2   556.4   991.5   585.5  992.79   604.9 1001.04
   653.5 1012.45   672.9 1020.71     702 1038.76   740.9 1054.22   779.7 1065.47
#Mann= 3 , 0 , 0
       0     .06       0   402.3    .045       0   416.5      .1       0
Bank Sta=402.3,416.5
XS Rating Curve= 0 ,0
Exp/Cntr=0.3,0.1

Type RM Length L Ch R = 1 ,19159.8 ,131.8,130.4,128.9
XS GIS Cut Line= 4
     1815329.204      425777.617     1815370.871      425425.186
     1815377.815       425321.02     1815419.482      425003.311
#Sta/Elev= 30
       0 1057.19      69 1032.94   118.3 1012.15     138 1000.53   177.4  996.34
   187.3  991.09   216.9  968.17   226.7  962.12   246.4  962.32   305.6  957.71
   354.9  958.89   373.9  957.22   379.7   954.9   392.8  952.46   394.7  953.25
   411.8  960.44   421.3  962.18   440.3   963.3   459.3  967.92   517.5  975.14
     537  989.04   546.7  992.95   575.8   993.9   595.2 1003.18   634.1 1008.38
   653.5 1015.98   663.2 1022.72   682.6 1040.45   692.3 1045.74   779.7 1079.72
#Mann= 3 , 0 , 0
       0     .05       0   379.7    .045       0   394.7     .06       0
Bank Sta=379.7,394.7
XS Rating Curve= 0 ,0
Exp/Cntr=0.3,0.1

Type RM Length L Ch R = 1 ,19029.5 ,465.7,463.5,461.4
XS GIS Cut Line= 4
     1815480.246      426032.391     1815502.858      425561.452
     1815501.581      425352.573     1815503.299      425007.416
#Sta/Elev= 30
       0 1092.92     108 1073.58   245.6  1037.8   304.5 1016.02   343.8 1004.24
   363.4     995   412.6   988.9     442  966.12   451.8  961.47   551.1  959.22
   590.8  962.31   620.7  953.41   630.6  951.03   640.4  951.16   670.4   955.8
   700.1  967.06     710  976.48   719.8  981.74   739.5  983.27   749.4  986.29
   759.3  992.12   828.3  996.55   867.7 1007.48   887.5 1023.95   897.3 1035.51
   907.2 1044.49     917 1050.51   946.6 1064.38   986.1 1077.33  1025.5  1093.3
#Mann= 3 , 0 , 0
       0     .08       0   620.7    .045       0   640.4     .07       0
Bank Sta=620.7,640.4
XS Rating Curve= 0 ,0
Exp/Cntr=0.3,0.1

Type RM Length L Ch R = 1 ,18565.9 ,1363.6,1369.9,1376.1
XS GIS Cut Line= 4
     1816093.093      426288.034     1815971.565        425454.7
     1815952.034      425257.218     1815930.333      425003.311
#Sta/Elev= 30
       0  1051.1    29.7  1049.7    89.2 1040.47   208.1 1017.74   287.3 1012.76
   297.2 1011.13     317 1003.42   465.7  995.73   594.5  984.79   624.2  970.16
     644  969.02   663.8  964.06   683.6  963.18     753  965.58   822.3  964.07
   901.7  958.89   941.4  952.57   950.4   949.2   965.4  947.62   971.1  947.55
   981.1  952.48     991  963.22  1000.9  969.47  1020.8  973.23  1060.2  991.54
    1119 1011.68    1168 1034.99  1236.6 1063.98  1275.8 1077.85  1295.4 1087.08
#Mann= 3 , 0 , 0
       0      .1       0   950.4    .045       0   965.4      .1       0
Bank Sta=950.4,965.4
XS Rating Curve= 0 ,0
Exp/Cntr=0.3,0.1

Type RM Length L Ch R = 1 ,17196   ,407.2,414.3,421.2
XS GIS Cut Line= 3
     1817170.625      425884.221     1817212.595      425329.049
     1817312.422      424801.705
#Sta/Elev= 30
       0 1104.95    29.8 1097.56    59.6 1086.64   129.2 1074.09   149.1 1066.08
   248.6 1036.78   258.5 1032.94   268.4 1025.01   278.4 1021.57   367.9  999.73
   387.7  991.39   407.6  987.06   427.5  976.45   437.4  973.81   457.3  973.83
   467.3  970.36   487.2  955.44   497.1  951.58   546.8  941.49   656.2  940.29
     698  936.63   705.8  936.46     713  937.63   775.4  972.36   805.2  979.34
   924.5 1036.58   964.3 1048.13  1023.9 1059.81  1063.6  1064.2  1093.5 1063.89
#Mann= 3 , 0 , 0
       0      .1       0     698    .045       0     713      .1       0
Bank Sta=698,713
XS Rating Curve= 0 ,0
Exp/Cntr=0.3,0.1

Type RM Length L Ch R = 1 ,16781.7 ,208.6,202.2,196
XS GIS Cut Line= 4
     1817331.215      425949.326     1817504.826      425506.617
     1817665.417      425202.798     1817895.451      424807.832
#Sta/Elev= 30
       0 1093.79     9.9 1090.82    49.5 1088.28   138.7 1069.14   227.9 1046.16
   247.7 1038.12   287.3 1030.84   376.5 1002.04   445.8  993.45   455.7  989.56
   475.5  974.74   485.4  971.24     505  970.75   514.8  967.56   534.4  946.51
   554.1  942.23   563.9  935.65  572.59933.0161   573.6  932.71   588.6  935.06
   603.2  938.83     721  940.52   750.4  944.06   839.1  946.17   888.7  951.35
   898.7  953.43   948.4   973.7  1037.8  992.87  1176.9 1007.73  1276.2 1024.94
#Mann= 3 , 0 , 0
       0      .1       0  572.59    .045       0   588.6    .055       0
Bank Sta=572.59,588.6
XS Rating Curve= 0 ,0
Exp/Cntr=0.3,0.1

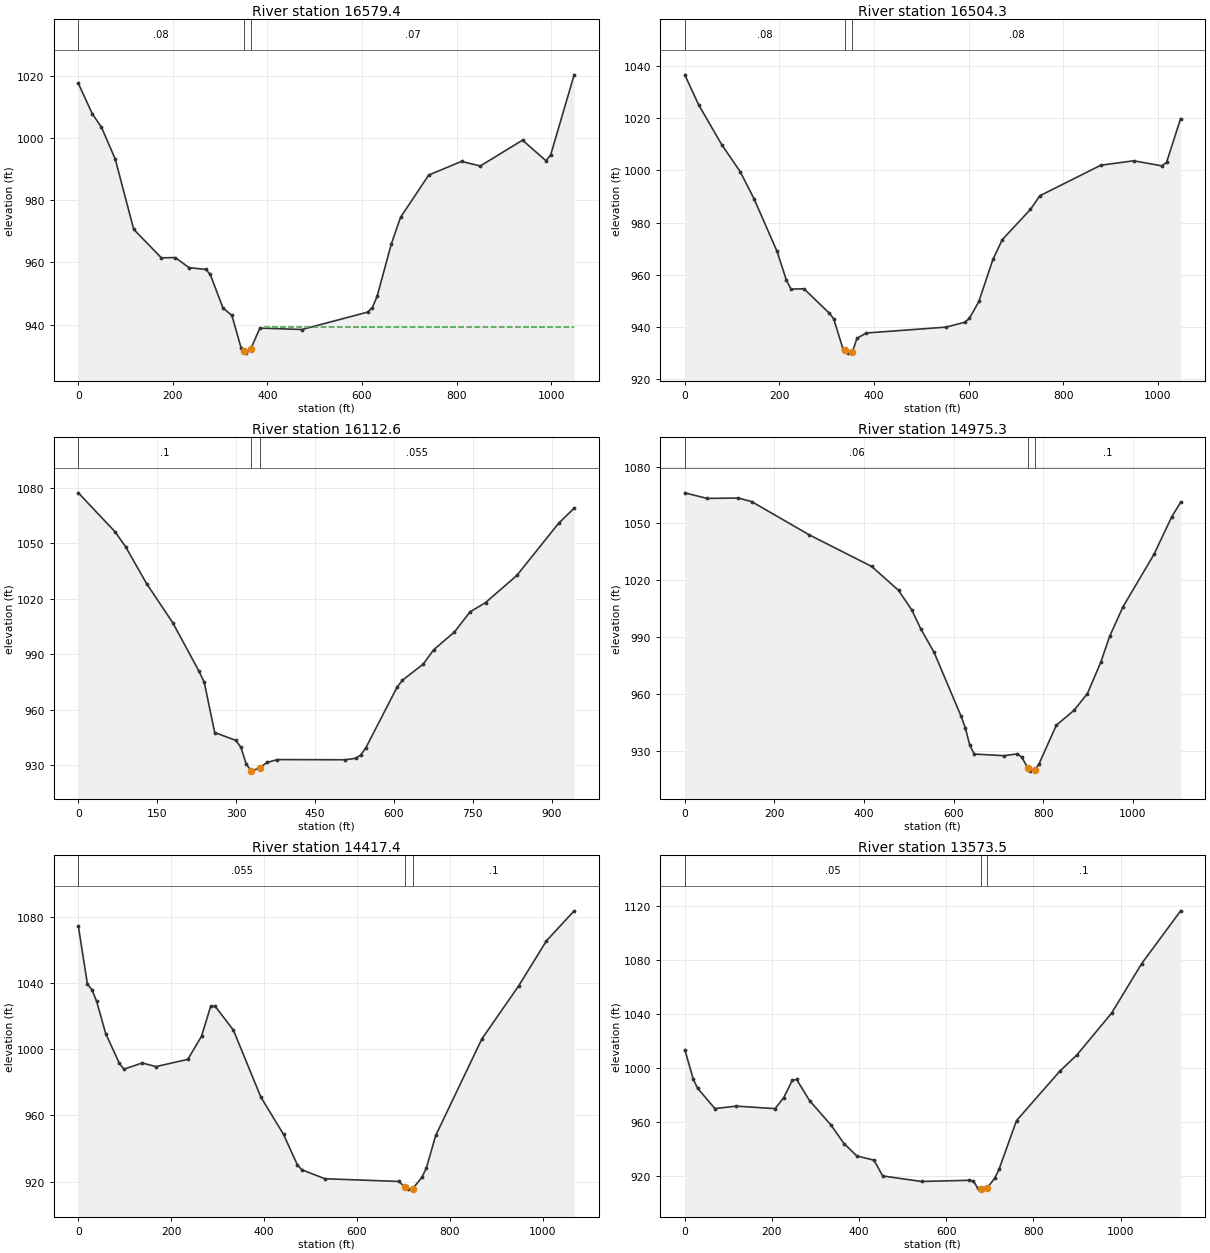
Type RM Length L Ch R = 1 ,16579.4 ,74.4,75.1,75.8
XS GIS Cut Line= 5
     1817801.137      425859.865     1817737.335      425634.605
     1817718.672      425556.046     1817746.884      425441.028
     1818024.661      424891.983
#Sta/Elev= 30
       0 1017.61    29.3 1007.89    48.8 1003.52      78  993.28   117.1  970.66
   175.6  961.48   204.9  961.56   234.1  958.33     270  957.74     279  956.12
   305.9  945.34   324.7  942.96   344.5  932.35   349.6  931.55   354.3  930.82
   364.6  932.16     384  938.88     473  938.42   611.9  944.02   621.9  945.49
   631.8  949.06   661.6  965.77   681.4   974.5     741  988.11   810.4  992.51
   850.1  991.03   939.4  999.34   989.1  992.71     999  994.62  1048.6 1020.36
#Mann= 3 , 0 , 0
       0     .08       0   349.6    .045       0   364.6     .07       0
#XS Ineff= 2 , 0
                          393.95          939.28
Permanent Ineff=
       F       F
Bank Sta=349.6,364.6
XS Rating Curve= 0 ,0
Exp/Cntr=0.3,0.1

Type RM Length L Ch R = 1 ,16504.3 ,387.4,391.7,397
XS GIS Cut Line= 5
     1817868.845      425885.907     1817805.043      425660.646
      1817786.38      425582.087     1817814.592       425467.07
      1818092.37      424918.025
#Sta/Elev= 30
       0  1036.6    29.3 1025.12      78  1009.9   117.1  999.56   146.3  989.21
   195.1  969.02   214.6  958.16   224.4   954.6   252.1  954.69   305.9  945.33
   314.9   943.2   334.6  931.71   338.3   931.1   344.5  930.08   354.3  930.46
   364.2  935.78     384  937.78   552.4  940.03   592.1   941.9     602  943.38
   621.9  949.85   651.6  965.92   671.5  973.54     731   985.1   750.9  990.31
   879.9 1002.01   949.4  1003.7  1008.9 1001.76  1018.8 1003.06  1048.6 1019.86
#Mann= 3 , 0 , 0
       0     .08       0   338.3    .045       0   354.3     .08       0
Bank Sta=338.3,354.3
XS Rating Curve= 0 ,0
Exp/Cntr=0.3,0.1

Type RM Length L Ch R = 1 ,16112.6 ,1144.4,1137.3,1128.8
XS GIS Cut Line= 3
     1818019.019      426007.869     1818155.738      425697.539
     1818424.835      425157.174
#Sta/Elev= 30
       0 1077.25    69.8 1056.19    89.8 1048.15   129.7  1028.2   179.5 1007.04
   229.4   980.8   239.4  974.82   259.3  947.64   299.2  943.42   309.2  939.63
   319.2  930.58  328.51926.9877   329.1  926.76   344.5  928.53   358.9  931.46
   378.7  933.01   507.4   932.9   527.1  933.68     537  935.44   546.9  939.48
   606.3  972.26   616.2   975.9   655.8  984.62   675.6  992.36   715.2 1002.02
   744.8 1012.87   774.5 1017.93   833.9 1032.61   913.1 1060.74   942.8 1068.96
#Mann= 3 , 0 , 0
       0      .1       0  328.51    .045       0   344.5    .055       0
Bank Sta=328.51,344.5
XS Rating Curve= 0 ,0
Exp/Cntr=0.3,0.1

Type RM Length L Ch R = 1 ,14975.3 ,575.2,557.9,540.7
XS GIS Cut Line= 4
     1819053.741       426712.73     1819240.373       426094.24
     1819259.904      425911.949     1819291.347      425636.162
#Sta/Elev= 30
       0 1066.17    49.7 1063.21   119.3 1063.43   149.1 1061.55   278.3 1043.92
   417.4 1027.27   477.1 1014.67   506.9 1004.25   526.8   994.3   556.6  981.88
   616.2  948.51   626.2  942.09   636.1  932.95     646   928.2   713.6  927.32
   742.5  928.33   752.2  926.56   765.9  920.82   771.5  919.18   780.9  919.58
   790.8  923.01   829.4  943.43     869  951.29   898.8  960.14   928.5  976.59
   948.3  990.31   978.1 1005.91  1047.5  1033.7  1087.1 1053.54  1106.9 1061.16
#Mann= 3 , 0 , 0
       0     .06       0   765.9    .045       0   780.9      .1       0
Bank Sta=765.9,780.9
XS Rating Curve= 0 ,0
Exp/Cntr=0.3,0.1

Type RM Length L Ch R = 1 ,14417.4 ,832.3,843.9,854.7
XS GIS Cut Line= 3
     1820162.682      426419.327     1819876.278      426032.373
     1819511.641      425572.973
#Sta/Elev= 30
       0  1074.3    19.6 1039.21    29.5 1035.77    39.3 1028.88      59 1009.32
    88.4  991.41    98.2  987.86   137.6  991.65     167  989.42   235.8  993.83
   265.3 1007.73   284.9 1025.76   294.7 1025.84     334 1011.45     393  971.09
   442.1  948.46   471.6  930.22   481.4  927.15   531.1  921.76   690.2  920.12
     704  916.54   710.1  915.49     720  915.75   739.9  922.54   749.8  928.42
   769.7  947.86   869.1 1006.13   948.6 1038.26  1008.3 1065.36  1067.9 1083.45
#Mann= 3 , 0 , 0
       0    .055       0     704    .045       0     720      .1       0
Bank Sta=704,720
XS Rating Curve= 0 ,0
Exp/Cntr=0.3,0.1

Type RM Length L Ch R = 1 ,13573.5 ,1081.2,1089.2,1097.2
XS GIS Cut Line= 3
     1820579.349      426106.827      1820499.06      425649.981
     1820378.828      424987.035
#Sta/Elev= 30
       0 1013.42    19.7  991.36    29.6  984.74    69.1  969.77   118.4  971.59
   207.2  969.72     227  977.87   246.7  990.78   256.6  991.36   286.2  975.68
   335.6  957.49   365.2  943.86   394.8  934.66   434.2  931.49     454  919.81
   543.1  915.72   652.1  916.58     662  916.12   671.9  910.93   679.5  910.25
   681.8  910.04   694.5  911.18   711.6   918.4   721.5   925.2   761.1  960.89
   860.2  997.42   899.8 1009.63   979.1 1040.48  1048.4 1077.34  1137.6  1116.4
#Mann= 3 , 0 , 0
       0     .05       0   679.5    .045       0   694.5      .1       0
Bank Sta=679.5,694.5
XS Rating Curve= 0 ,0
Exp/Cntr=0.3,0.1

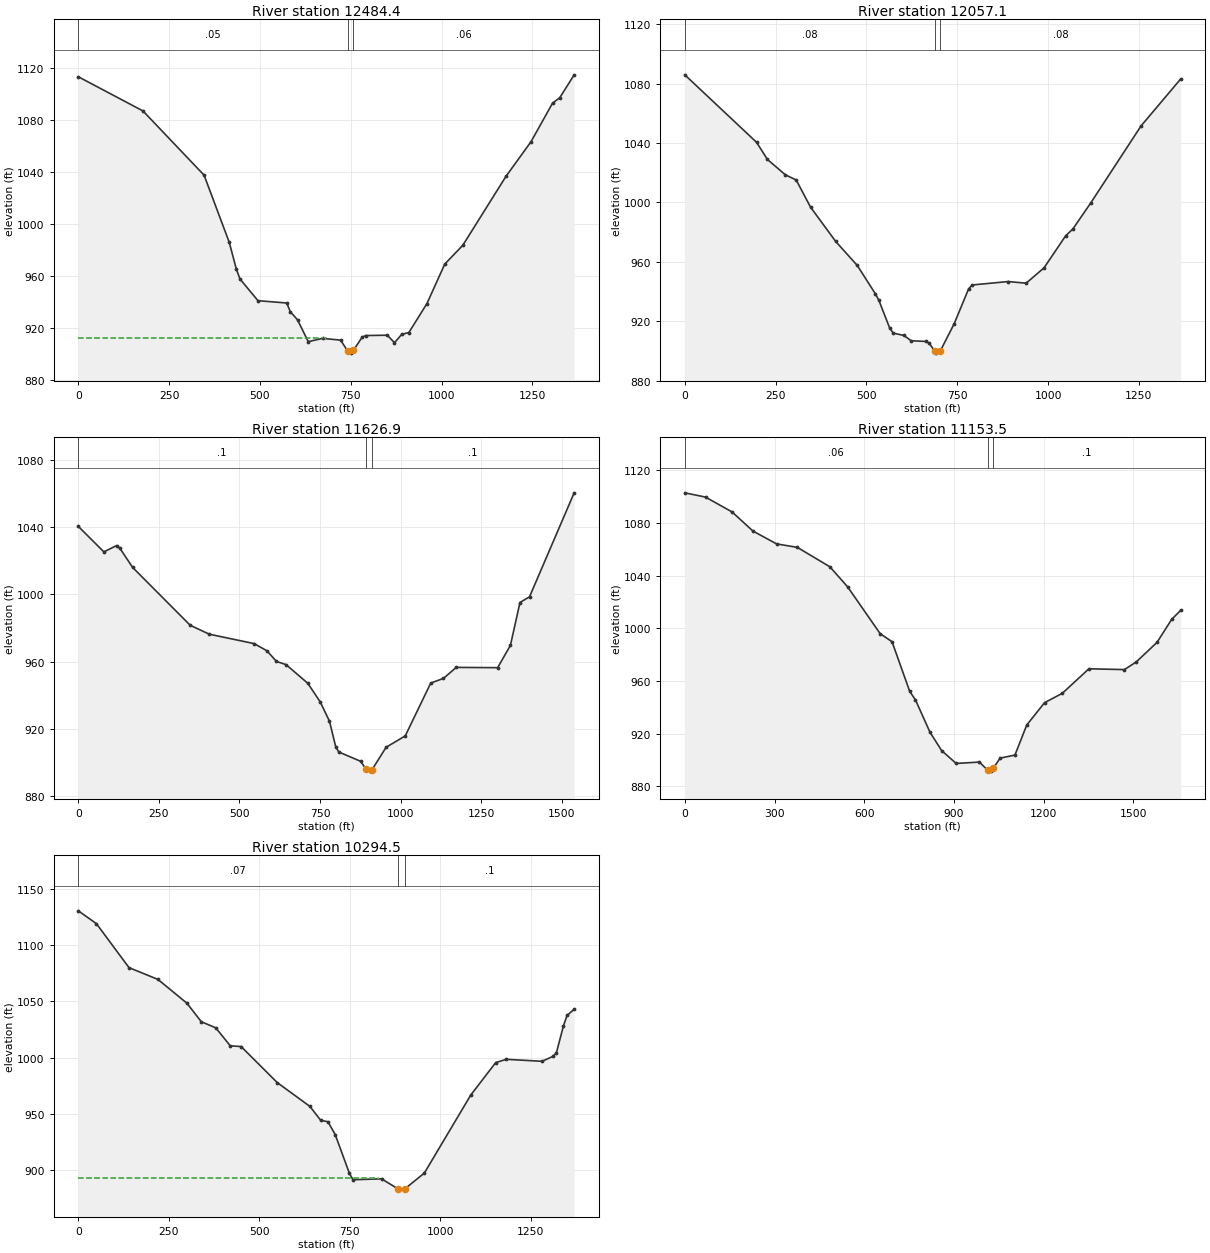
Type RM Length L Ch R = 1 ,12484.4 ,422.4,427.3,432.1
XS GIS Cut Line= 3
     1821406.694      426097.688     1821527.756      425426.011
     1821648.818      424754.333
#Sta/Elev= 30
       0 1113.08     178 1086.84   346.2 1037.56   415.4  986.08   435.2  965.26
   445.1  957.84   494.6  941.24   573.7  939.46   583.6  932.77   603.4  926.55
     633  909.79   672.6  912.31   722.1  910.96   741.8  902.47   751.7  900.99
   757.3  903.11   781.4  913.24   791.3  914.49   850.6  914.74   870.4  908.98
   890.2  915.35     910  916.82   959.5  938.91  1008.9  969.38  1058.4  983.72
  1177.1 1036.58  1246.3 1063.28  1305.6 1092.88  1325.4 1097.01    1365 1114.57
#Mann= 3 , 0 , 0
       0     .05       0   741.8    .045       0   757.3     .06       0
#XS Ineff= 2 , 0
           682.6  912.36  792.06          914.43
Permanent Ineff=
       F       F
Bank Sta=741.8,757.3
XS Rating Curve= 0 ,0
Exp/Cntr=0.3,0.1

Type RM Length L Ch R = 1 ,12057.1 ,441.3,430.2,419.1
XS GIS Cut Line= 3
     1821697.089      426051.692     1821957.443      425420.802
     1822217.798      424789.913
#Sta/Elev= 30
       0  1085.9   197.8 1040.43   227.5 1028.93     277 1018.58   306.6 1015.15
   346.2  996.86   415.4  973.77   474.8  957.62   524.2   938.7   534.1  934.27
   563.8  915.65   573.7  912.08   603.4  910.49   623.2  906.94   662.7  906.48
   672.6  905.34   688.4  899.92   692.4  898.61   703.4  900.06   741.8  918.48
   781.4   941.9   791.3  944.48   890.2  946.78   939.7  945.68   989.1  956.04
  1048.5  977.57  1068.3  982.15  1117.7  999.73  1256.2 1051.56    1365 1083.07
#Mann= 3 , 0 , 0
       0     .08       0   688.4    .045       0   703.4     .08       0
Bank Sta=688.4,703.4
XS Rating Curve= 0 ,0
Exp/Cntr=0.3,0.1

Type RM Length L Ch R = 1 ,11626.9 ,479.4,473.4,467.4
XS GIS Cut Line= 4
     1822344.974      426341.202     1822378.828      425687.556
     1822381.922      425485.906     1822318.274      424806.381
#Sta/Elev= 30
       0 1040.41    79.3 1025.26     119 1029.04   128.9 1027.42   168.6 1016.02
   347.1  981.66   406.6  976.34   545.4  970.77   585.1  966.53   614.8  960.18
   644.6  958.26   712.1  947.19   750.6  936.13   779.4  924.65   798.6   909.6
   808.2  906.34     876  900.83  891.57896.5132   905.6  894.98     910  895.39
   955.1  909.15  1014.5  915.91  1093.6   947.3  1133.2  950.09  1172.7  956.62
  1301.3  956.46  1340.9  969.72  1370.5  995.17  1400.2  998.58  1538.7 1060.36
#Mann= 3 , 0 , 0
       0      .1       0  891.57    .045       0     910      .1       0
Bank Sta=891.57,910
XS Rating Curve= 0 ,0
Exp/Cntr=0.3,0.1

Type RM Length L Ch R = 1 ,11153.5 ,858.1,859,860.1
XS GIS Cut Line= 4
     1823170.495      426273.494     1822931.116      425581.347
     1822845.419      425354.252     1822604.458      424715.703
#Sta/Elev= 30
       0  1102.8    69.3 1099.56   158.4 1088.23   227.6 1073.81   306.8 1064.02
   376.1 1061.39     485 1046.65   544.3 1031.44   653.2  995.84   692.8  989.75
   751.8  952.11   771.2  945.54   819.8  920.98   858.6  907.11   907.1  897.32
     985  898.35 1012.32892.1936  1024.6  891.48    1031  893.59  1054.2  901.35
  1103.7  903.67  1143.2  926.49  1202.6  943.43    1262  950.56    1351  969.18
  1469.7  968.58  1509.2  974.38  1578.5   989.2  1627.9 1006.78  1657.6 1013.52
#Mann= 3 , 0 , 0
       0     .06       0 1012.32    .045       0    1031      .1       0
Bank Sta=1012.32,1031
XS Rating Curve= 0 ,0
Exp/Cntr=0.3,0.1

Type RM Length L Ch R = 1 ,10294.5 ,1205.4,1189.8,1175.9
XS GIS Cut Line= 3
     1823847.578       425739.64     1823626.224       425065.16
     1823420.495      424437.556
#Sta/Elev= 30
       0  1130.3      50 1118.92     140 1079.91     220 1069.43     300 1048.37
   339.9 1031.88   379.9 1026.47   419.9 1010.52   449.9 1009.87   549.9  977.85
   639.9  956.79   669.9   944.4   689.9  943.15   709.9  931.77   749.3  897.24
   759.2  891.68     838   892.5  882.32883.8074   897.2  883.36   902.9  883.75
   956.3  897.61  1084.5   966.8  1153.5  995.65    1183  998.54  1281.6  996.79
  1311.2 1001.08    1321 1004.07  1340.8  1028.3  1350.6 1037.46  1370.3 1042.97
#Mann= 3 , 0 , 0
       0     .07       0  882.32    .045       0   902.9      .1       0
#XS Ineff= 2 , 0
          828.67  892.88
Permanent Ineff=
       F       F
Bank Sta=882.32,902.9
XS Rating Curve= 0 ,0
Exp/Cntr=0.3,0.1