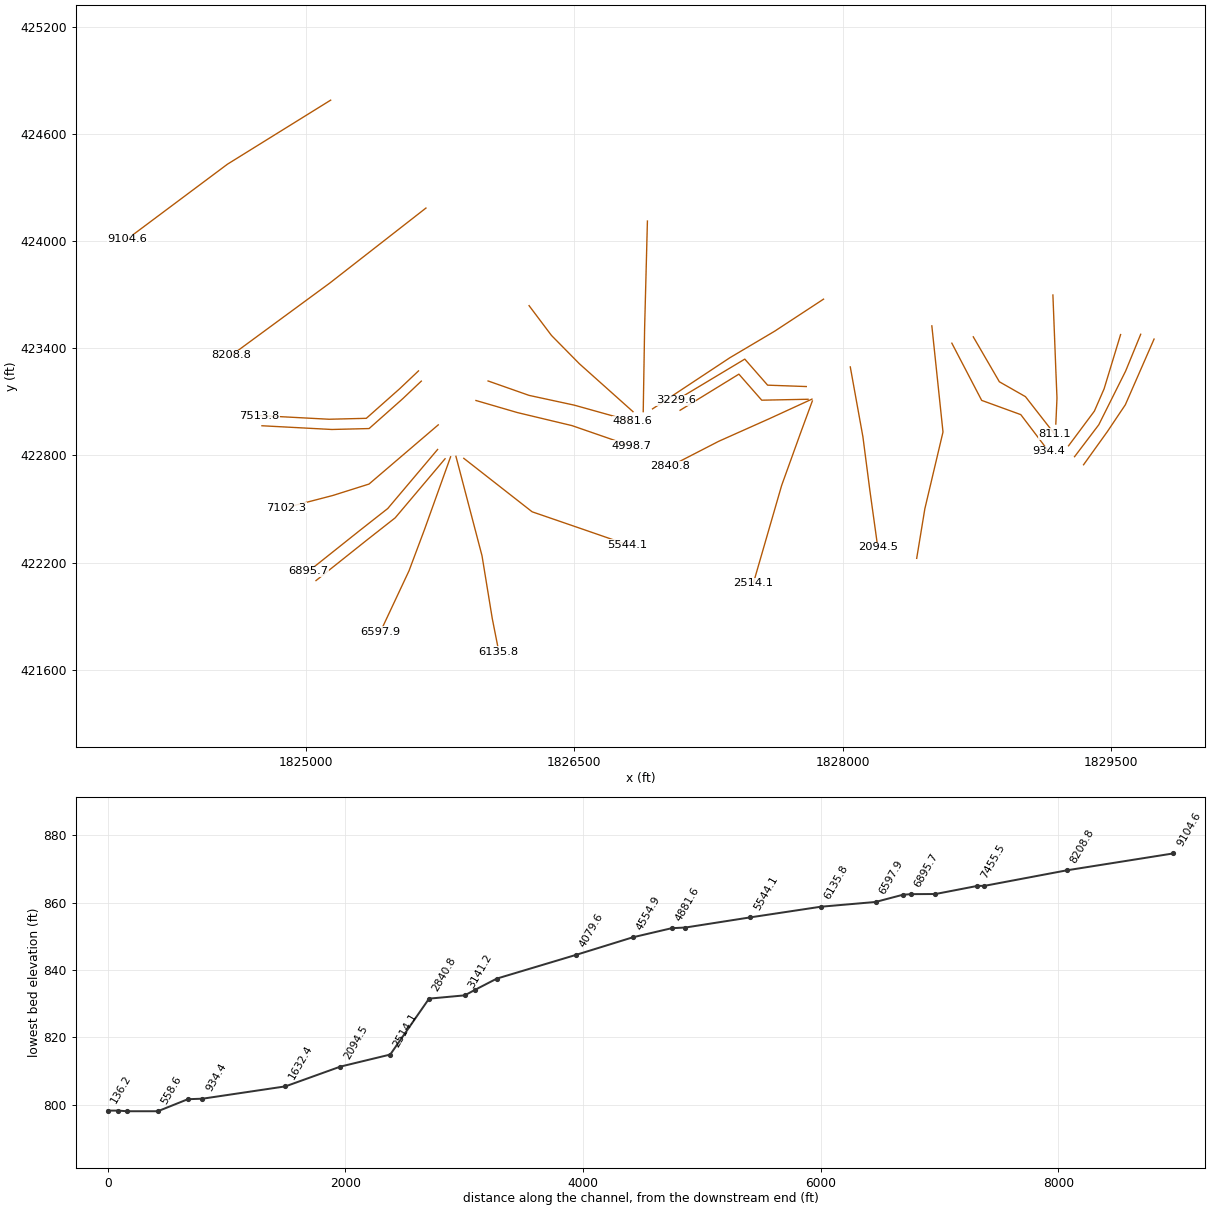
HEC-RAS study ScottsRun.prj: ScottsRun

--- ScottsRun.g01 (geometry) --- (continued)

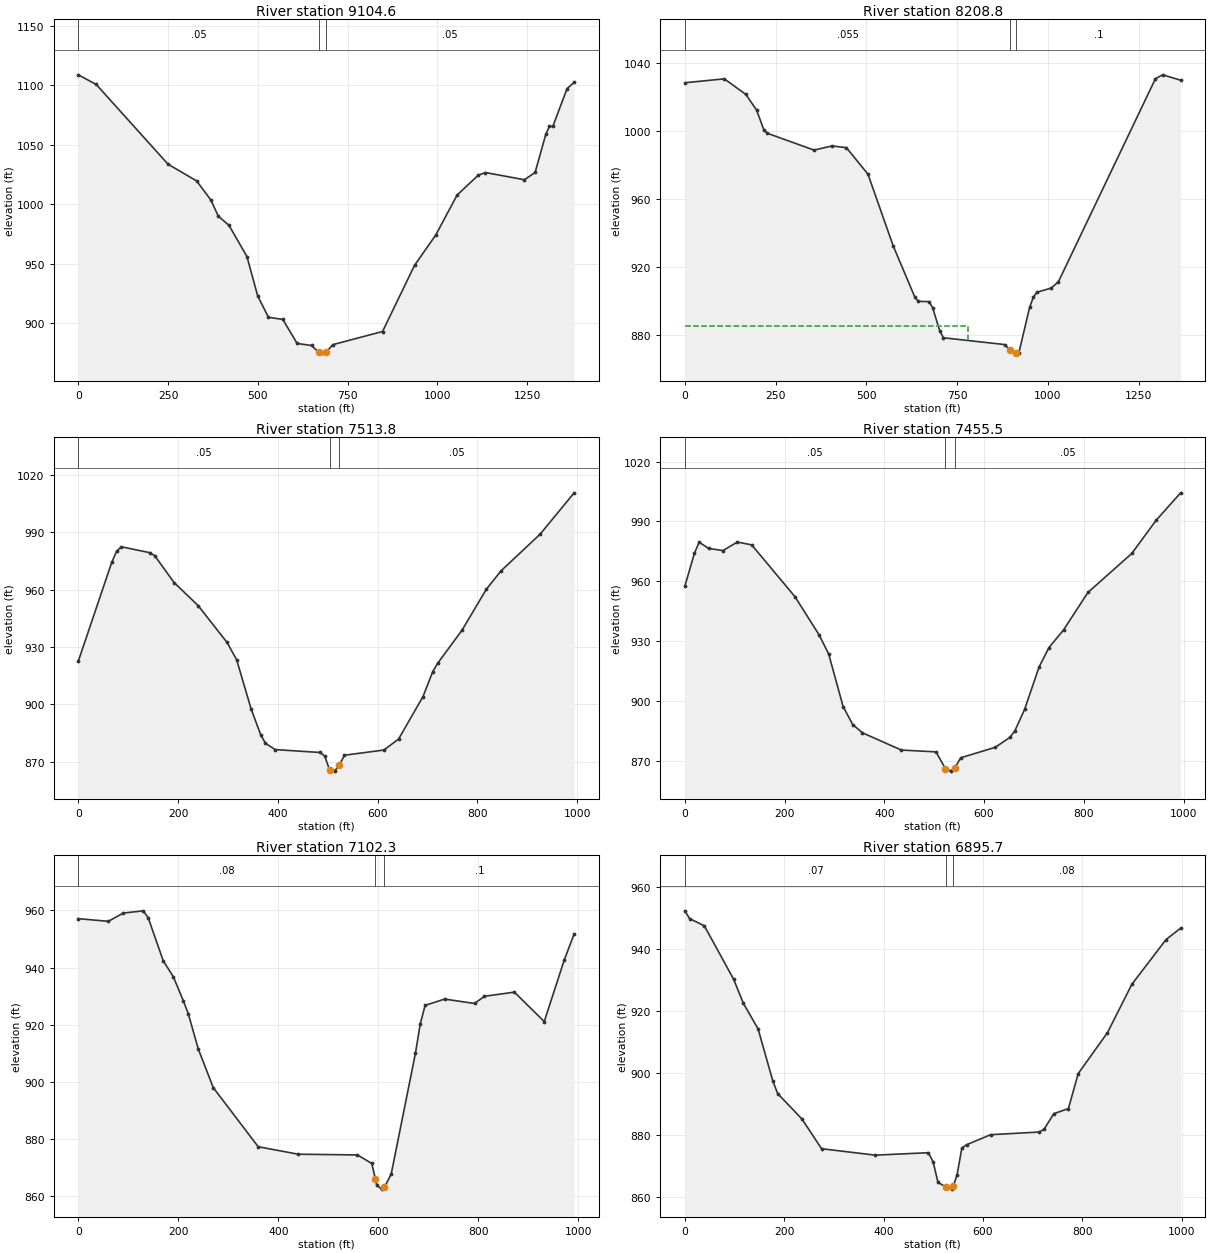
Type RM Length L Ch R = 1 ,9104.6  ,894.1,895.9,895.7
XS GIS Cut Line= 3
     1825137.817      424789.998     1824561.113      424431.381
     1823999.605      424011.063
#Sta/Elev= 30
       0 1108.73    49.9  1100.6   249.7 1033.57   329.6 1019.42   369.5 1003.18
   389.5  989.92   419.4  982.13   469.4  955.89   499.4  922.71   529.3  904.78
   569.3  902.96   609.2  882.73   649.2  881.04   669.1  875.39   679.1  874.61
     689  875.28   708.8  881.76     847   892.8     936  948.42   995.2  973.96
  1054.5 1007.57  1113.8 1024.39  1133.5 1026.52  1242.2 1020.46  1271.8 1026.62
  1301.5 1058.68  1311.4 1065.29  1321.2 1065.41  1360.8 1097.16  1380.5 1102.35
#Mann= 3 , 0 , 0
       0     .05       0   669.1    .045       0     689     .05       0
Bank Sta=669.1,689
XS Rating Curve= 0 ,0
Exp/Cntr=0.3,0.1

Type RM Length L Ch R = 1 ,8208.8  ,708.7,695,681.2
XS GIS Cut Line= 3
     1825670.441      424185.594     1825132.765      423765.325
      1824582.79       423360.59
#Sta/Elev= 30
       0 1028.34   108.8 1030.64   168.1  1021.5   197.8 1012.25   217.6 1000.74
   227.5  998.68     356   988.8   405.5  991.25   445.1  990.23   504.4  974.64
   573.6  932.71     633  902.69   642.9     900   672.6  899.84   682.4  896.24
   702.2  882.62   712.1  878.62   880.4  874.64   896.8  871.21     910   869.6
   911.8  869.65     920  869.89   949.6  896.54   959.5   902.3   969.4  905.33
    1009  907.81  1028.8  911.52    1296 1030.74  1315.8    1033  1365.3 1029.84
#Mann= 3 , 0 , 0
       0    .055       0   896.8    .045       0   911.8      .1       0
#XS Ineff= 2 , 0
          781.19   885.5
Permanent Ineff=
       F       F
Bank Sta=896.8,911.8
XS Rating Curve= 0 ,0
Exp/Cntr=0.3,0.1

Type RM Length L Ch R = 1 ,7513.8  ,58.2,58.2,58.2
XS GIS Cut Line= 5
     1825628.828      423273.494     1825524.661      423174.535
     1825337.161      423007.869     1825128.828       423002.66
     1824738.203      423023.494
#Sta/Elev= 30
       0  922.56      67  974.24    76.6  979.96    86.2  982.41   143.7  979.28
   153.3  977.67   191.9  963.69   240.2  951.61   298.1  932.35   317.4  923.29
   346.3  897.63   365.6  884.04   375.2  879.56   394.5  876.26   483.9  874.75
   493.8  872.98   503.7  865.61   513.6  864.98   523.5  868.18   533.5   873.3
   612.7  876.03   642.1  881.79     691  903.97   710.5  917.01   720.3  921.38
   769.2   938.7   818.1  960.19   847.4  969.77   925.7  988.94   994.1 1010.63
#Mann= 3 , 0 , 0
       0     .05       0   503.7    .045       0   523.5     .05       0
Bank Sta=503.7,523.5
XS Rating Curve= 0 ,0
Exp/Cntr=0.3,0.1

Type RM Length L Ch R = 1 ,7455.5  ,347,353.3,359.5
XS GIS Cut Line= 5
     1825644.453      423216.202     1825540.286      423117.244
     1825352.786      422950.577     1825144.453      422945.369
     1824753.828      422966.202
#Sta/Elev= 30
       0  957.51    19.2     974    28.7  979.64    47.9  976.49    76.6  975.45
   105.4  979.71   134.1  978.29   220.9  952.34   269.1  933.28   288.4   923.7
   317.4  897.32   336.6  888.32     356  884.18   434.2  875.53   503.7  874.61
  522.53866.2017   533.5  864.97   541.3   866.6   553.3  871.66   622.5   876.9
   651.8  881.87   661.6  885.08   681.2  895.84   710.5  917.24   730.1  926.84
   759.4   935.7   808.3  954.47   896.3  974.01   945.2  990.67   994.1 1004.36
#Mann= 3 , 0 , 0
       0     .05       0  522.53    .045       0   541.3     .05       0
Bank Sta=522.53,541.3
XS Rating Curve= 0 ,0
Exp/Cntr=0.3,0.1

Type RM Length L Ch R = 1 ,7102.3  ,198.4,206.6,214.8
XS GIS Cut Line= 4
     1825739.263      422971.231      1825352.11      422639.634
     1825148.985      422575.398     1824888.569       422507.69
#Sta/Elev= 30
       0  957.07      60  956.14      90  959.03   129.9  959.81   139.9  957.34
   169.9  942.33   189.9  936.81   209.9  928.46   219.9   923.9   239.9  911.55
   269.9  898.03   359.8  877.38   439.8  874.76   558.2  874.51   587.2  871.52
   594.2  866.06   596.9  863.95   606.6  862.56  612.45  863.15     626  867.92
   674.4  910.05     684   920.3   693.7  926.77   732.8  928.97   792.6  927.44
   812.5  929.94   872.3   931.4   932.1  921.12   971.9  942.53   991.9  951.77
#Mann= 3 , 0 , 0
       0     .08       0   594.2    .045       0  612.45      .1       0
Bank Sta=594.2,612.45
XS Rating Curve= 0 ,0
Exp/Cntr=0.3,0.1

Type RM Length L Ch R = 1 ,6895.7  ,67.9,67.9,67.9
XS GIS Cut Line= 4
     1825735.599       422833.39     1825456.953       422502.66
     1825298.099       422377.66     1825014.245      422151.098
#Sta/Elev= 30
       0  952.46     9.8  949.93    39.3  947.62    98.3  930.34   117.9  922.56
   147.4  914.33   176.9  897.61   186.8  893.42   235.9  885.16   275.2  875.58
   383.3   873.5   490.2  874.29   499.8   871.3   509.5  864.69   525.5  863.22
   538.4  862.52   540.5  863.55     548  867.23   557.6  875.81   567.2  876.87
   615.4  880.11   713.1  880.97   722.9  881.84   742.6   886.9     772  888.55
   791.7  899.86   850.6  913.09   899.6  928.69   968.3  943.15   997.8  946.85
#Mann= 3 , 0 , 0
       0     .07       0   525.5    .045       0   540.5     .08       0
Bank Sta=525.5,540.5
XS Rating Curve= 0 ,0
Exp/Cntr=0.3,0.1

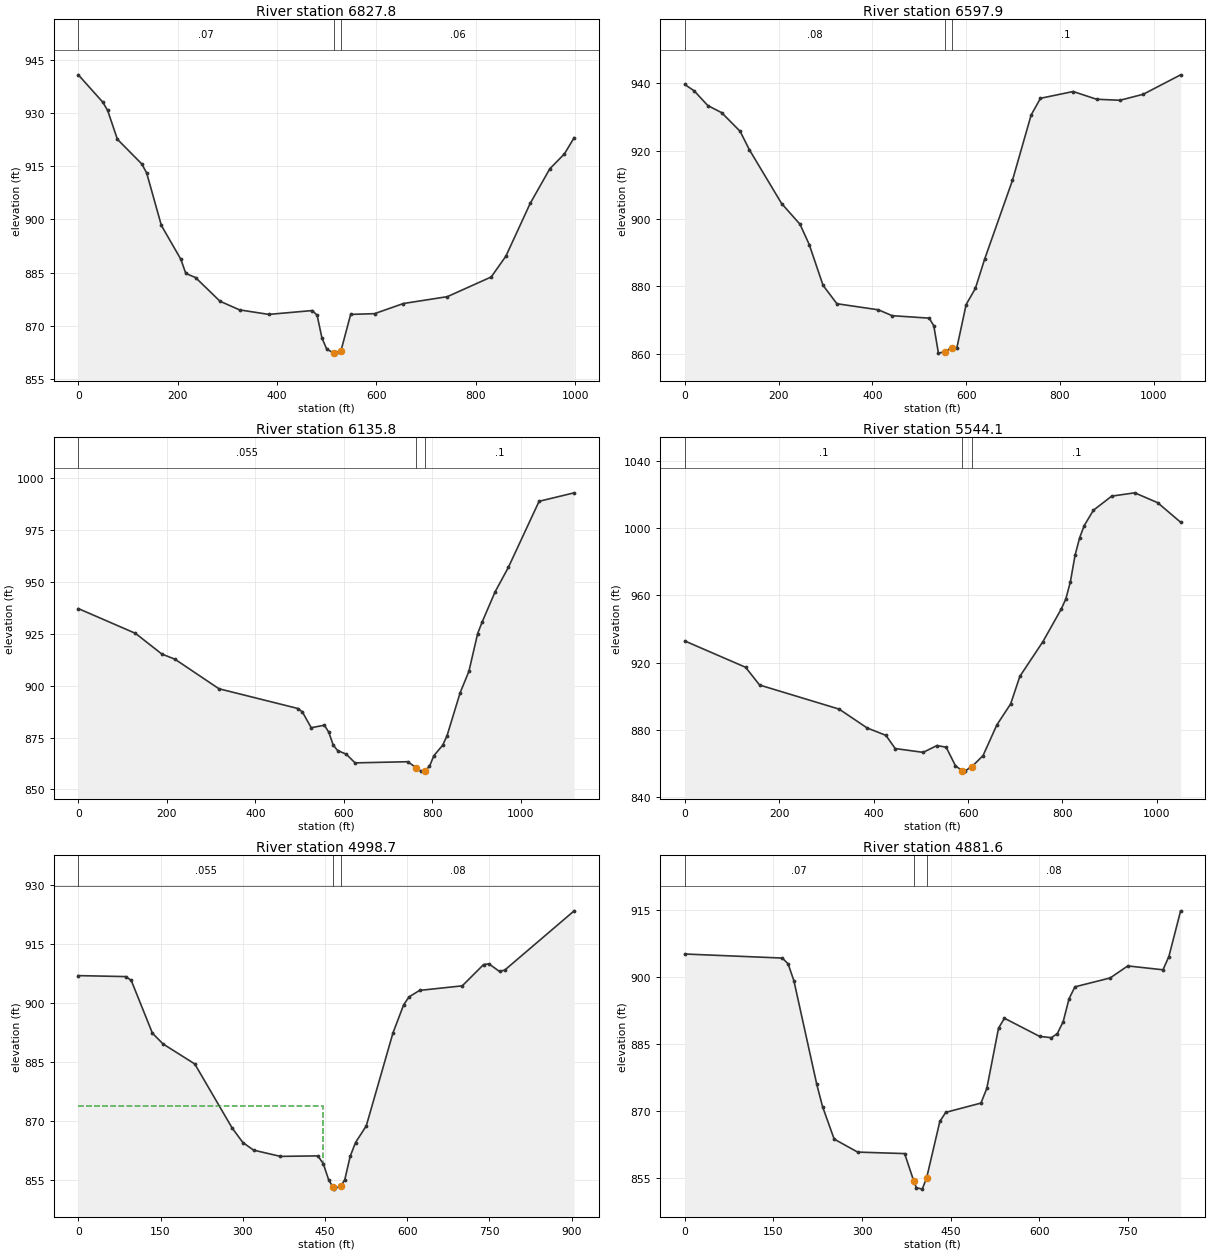
Type RM Length L Ch R = 1 ,6827.8  ,217.4,229.9,242.3
XS GIS Cut Line= 4
     1825777.266      422781.306      1825498.62      422450.577
     1825339.766      422325.577     1825055.911      422099.015
#Sta/Elev= 30
       0  940.75    49.1  933.06      59  930.72    78.6  922.59   127.8  915.63
   137.6  913.06   167.1  898.32   206.4  888.76   216.2   884.8   235.9  883.63
     285  876.97   324.4  874.53   383.3  873.25     471  874.34   480.6  872.97
   490.2  866.64   499.8  863.48   513.5  862.39   519.1  862.34   528.5  862.97
     548  873.25   596.1  873.46   654.2  876.32   742.6  878.25   830.9   883.8
   860.4  889.66   909.4  904.55   948.7  914.26   978.2  918.48   997.8  923.04
#Mann= 3 , 0 , 0
       0     .07       0   513.5    .045       0   528.5     .06       0
Bank Sta=513.5,528.5
XS Rating Curve= 0 ,0
Exp/Cntr=0.3,0.1

Type RM Length L Ch R = 1 ,6597.9  ,450.2,462.2,474.1
XS GIS Cut Line= 4
     1825808.274      422792.412     1825662.394      422385.174
     1825576.069      422154.391     1825415.479      421811.509
#Sta/Elev= 30
       0  939.69    19.7  937.85    49.2  933.44    78.6  931.36     118  925.84
   137.6  920.42   206.5  904.47   245.8  898.32   265.4  892.34   294.9  880.26
   324.4  874.82   412.9  873.02   442.4  871.28   521.3  870.55   531.1   868.3
     541   860.2   554.5   860.6   569.5   861.8   580.4  861.83   600.1  874.57
   619.8  879.36   639.6  888.02   698.9  911.33   738.8  930.68   758.7  935.61
   828.4  937.61   878.2  935.33   928.1  935.02   977.9   936.8  1057.6  942.55
#Mann= 3 , 0 , 0
       0     .08       0   554.5    .045       0   569.5      .1       0
Bank Sta=554.5,569.5
XS Rating Curve= 0 ,0
Exp/Cntr=0.3,0.1

Type RM Length L Ch R = 1 ,6135.8  ,567.2,591.7,616.1
XS GIS Cut Line= 4
     1825838.029      422795.195     1825983.863      422237.903
     1826041.154      421886.341     1826077.613      421701.445
#Sta/Elev= 30
       0  937.19   129.1  925.25   188.7  915.27   218.5  912.76   317.8  898.52
   496.6  888.98   506.5   887.3   526.4  879.72   556.2  880.94   566.1  877.54
   576.1  871.37     586  868.72   605.7  866.94   625.5  862.76   744.3  863.32
     764  860.43     774  858.78     784  859.06   793.7  861.07   803.6  866.24
   823.4  871.25   833.3  875.81     863   896.6   882.8  906.93   902.6  925.17
   912.5  930.61   942.2  945.35   971.9  957.03  1041.4  988.94  1120.7  993.03
#Mann= 3 , 0 , 0
       0    .055       0     764    .045       0     784      .1       0
Bank Sta=764,784
XS Rating Curve= 0 ,0
Exp/Cntr=0.3,0.1

Type RM Length L Ch R = 1 ,5544.1  ,543.1,545.4,547.1
XS GIS Cut Line= 4
     1825882.058      422783.731     1826264.003      422484.252
     1826522.249      422395.276     1826797.857       422299.79
#Sta/Elev= 30
       0  932.98   128.8  917.34   158.5  906.79   326.9  892.48   386.3  881.27
   425.9   876.9   445.7  869.05   504.9  866.78   534.1  870.84   553.6  869.84
   573.2  858.87   587.8  855.76   592.7  855.63   608.2858.3162   631.7  864.87
     661  883.11   690.2   895.6   709.7  911.96   758.5  932.58   797.4  951.98
   807.1  957.97   816.8  968.29   826.6  983.92   836.3   994.3     846 1001.54
   865.4 1010.65   904.3 1019.06     953 1021.01  1001.6 1015.15  1050.2 1003.53
#Mann= 3 , 0 , 0
       0      .1       0   587.8    .045       0   608.2      .1       0
Bank Sta=587.8,608.2
XS Rating Curve= 0 ,0
Exp/Cntr=0.3,0.1

Type RM Length L Ch R = 1 ,4998.7  ,116.5,117.1,117.6
XS GIS Cut Line= 4
     1825950.009      423107.695     1826181.779      423039.987
     1826486.467       422967.07     1826817.196      422852.487
#Sta/Elev= 30
       0  906.93    86.9  906.68    96.6  905.69   135.2  892.29   154.5  889.56
   212.5  884.46   280.6  868.19   300.2  864.48   319.8  862.54   368.7  860.95
   437.3  861.08   447.1  859.04   456.8     855   464.5  853.13   466.6  852.62
   479.5  853.53   486.2  855.01     496  860.92   505.8  864.47   525.4  868.69
   574.2  892.37   593.6  899.48   603.4  901.52   622.8  903.17   700.6  904.33
   739.5  909.74   749.2  909.93   768.6  907.98   778.4  908.37   904.8  923.41
#Mann= 3 , 0 , 0
       0    .055       0   464.5    .045       0   479.5     .08       0
#XS Ineff= 2 , 0
          445.82   873.8
Permanent Ineff=
       F       F
Bank Sta=464.5,479.5
XS Rating Curve= 0 ,0
Exp/Cntr=0.3,0.1

Type RM Length L Ch R = 1 ,4881.6  ,340.4,326.6,313.3
XS GIS Cut Line= 4
     1826017.717       423217.07     1826246.884      423136.341
     1826499.488      423081.653     1826825.009      422990.508
#Sta/Elev= 30
       0  905.12   165.2  904.21   174.9  902.91   184.7  899.14   223.5  875.87
   233.2  870.92   252.9  863.63   292.7  860.71   372.2  860.38   387.6854.2437
   392.1  852.73     402  852.41  409.49854.9475   431.8  867.58   441.8  869.62
   501.4   871.7   511.4  875.01   531.2   888.5   541.2  890.72   600.8  886.65
   620.7  886.36   630.7  887.28   640.6  889.94   650.6  895.08   660.5  897.76
   720.2  899.75     750  902.45   809.6  901.58   819.6  904.55   839.5   914.8
#Mann= 3 , 0 , 0
       0     .07       0   387.6    .045       0  409.49     .08       0
Bank Sta=387.6,409.49
XS Rating Curve= 0 ,0
Exp/Cntr=0.3,0.1

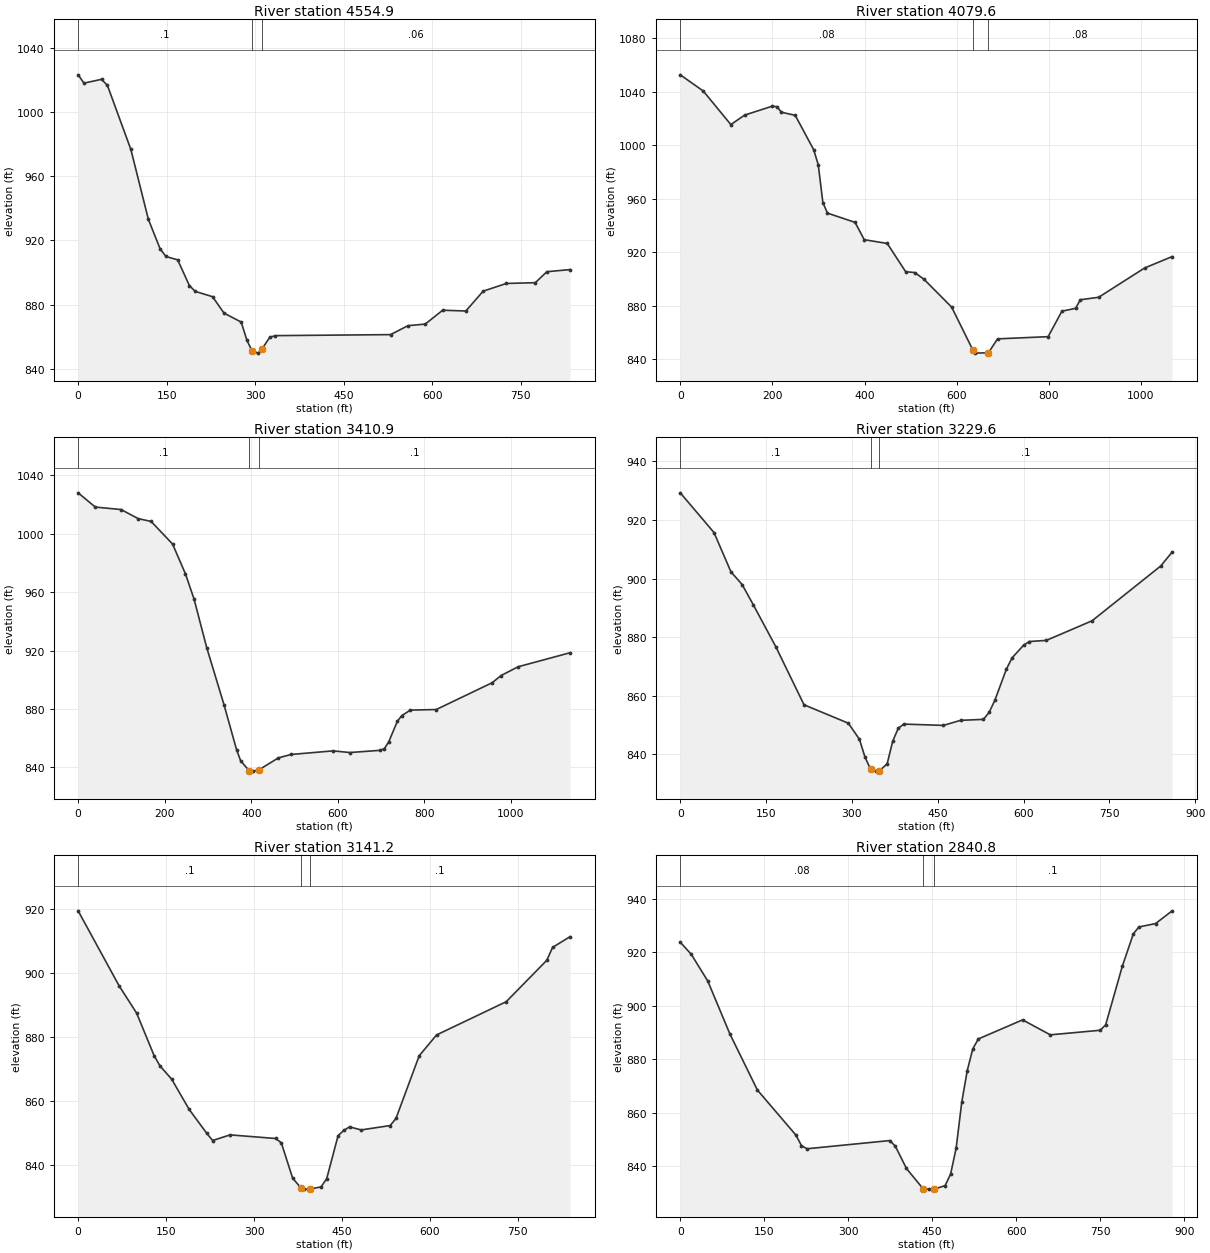
Type RM Length L Ch R = 1 ,4554.9  ,493.2,475.3,457.2
XS GIS Cut Line= 4
     1826246.884      423638.945     1826371.884      423472.278
     1826528.134      423313.424     1826827.613      423045.195
#Sta/Elev= 30
       0 1023.26     9.9 1018.08    39.7 1020.46    49.6 1016.67    89.3  976.73
     119   933.1   138.9  914.73   148.8  909.97   168.6  907.88   188.5   891.8
   198.4  888.21   227.7   884.9   247.1  874.67   276.2  869.07   285.8  857.84
  294.65850.9881   305.2  849.71   311.5  852.33   324.6   859.6   334.3  860.62
   529.2  861.25   558.6  866.82     588  867.83   617.5  876.47   656.7  875.98
   686.1  888.36   725.3  893.15   774.4  893.64     794  900.49   833.2   901.8
#Mann= 3 , 0 , 0
       0      .1       0  294.65    .045       0   311.5     .06       0
Bank Sta=294.65,311.5
XS Rating Curve= 0 ,0
Exp/Cntr=0.3,0.1

Type RM Length L Ch R = 1 ,4079.6  ,692.2,668.7,645.4
XS GIS Cut Line= 3
     1826908.342      424112.903     1826892.717      423513.945
     1826884.904      423045.195
#Sta/Elev= 30
       0 1052.71    49.9 1040.61   109.8 1015.49   139.8 1022.58   199.7 1029.26
   209.7 1028.89   219.7 1024.73   249.6 1022.41   289.6  996.72   299.6  985.46
   309.6  957.12   319.6  949.26   379.5  942.34   399.4  929.39   449.4  926.56
   489.3  905.46   509.3  904.77   529.3  899.73   589.2  878.96  635.47846.6944
   639.1  844.52     669  844.77   688.9  855.19   798.7  856.84   828.6  875.91
   858.5  878.05   868.5  884.44   908.4   886.3  1008.1   908.2    1068  916.75
#Mann= 3 , 0 , 0
       0     .08       0  635.47    .045       0     669     .08       0
Bank Sta=635.47,669
XS Rating Curve= 0 ,0
Exp/Cntr=0.3,0.1

Type RM Length L Ch R = 1 ,3410.9  ,214.2,181.3,148.1
XS GIS Cut Line= 4
     1827892.717      423675.403     1827619.279      423495.716
     1827369.279      423347.278     1826936.988       423060.82
#Sta/Elev= 30
       0 1027.94    39.7 1018.19    99.2  1016.5   138.8 1010.28   168.6 1008.37
   218.1  992.93   247.9  972.52   267.7  955.35   297.4  921.65   336.9  883.04
     366  852.16   375.6  844.45     395  837.84   404.7  837.46   418.6  838.52
   462.9  846.56     492  848.86   588.9  851.32   627.9  850.19   697.7  851.69
   707.7  852.89   717.7  857.58   737.6  871.58   747.6   875.4   767.5  879.22
   827.4  879.62     957  898.02     977  902.86  1016.8  908.91  1136.5  918.48
#Mann= 3 , 0 , 0
       0      .1       0     395    .045       0   418.6      .1       0
Bank Sta=395,418.6
XS Rating Curve= 0 ,0
Exp/Cntr=0.3,0.1

Type RM Length L Ch R = 1 ,3229.6  ,88.7,88.4,88
XS GIS Cut Line= 4
     1827796.363       423185.82     1827580.217      423193.633
     1827452.613      423339.466     1827067.196      423107.695
#Sta/Elev= 30
       0  929.29      59   915.7    88.5  902.31   108.1  897.94   127.8  890.97
   167.1  876.64   216.3  856.84   293.8  850.54   313.2  845.04   322.9  838.92
   332.6  834.84   342.2  834.16     348  834.24   361.6  836.66   371.3  844.36
     381  848.81   390.7  850.24     460  849.79     490  851.52     530  851.85
     540   854.3     550  858.43     570  869.02     580  872.88     600  877.18
     610  878.46   639.9  878.85   719.9  885.56   839.8  904.28   859.8  909.05
#Mann= 3 , 0 , 0
       0      .1       0   332.6    .045       0     348      .1       0
Bank Sta=332.6,348
XS Rating Curve= 0 ,0
Exp/Cntr=0.3,0.1

Type RM Length L Ch R = 1 ,3141.2  ,270.6,300.5,330.4
XS GIS Cut Line= 4
     1827806.345       423114.64     1827547.231      423109.431
     1827419.627      423255.265     1827091.068      423053.008
#Sta/Elev= 30
       0  919.55    69.8  896.11    99.7  887.57   129.6  874.24   139.6  871.02
   159.5  866.89   189.4  857.41   219.3  849.96   229.3   847.7   259.2  849.46
   336.7  848.33   346.4  847.01   365.8  835.93   380.8  832.69   385.1  832.49
   395.8  832.55   414.2  833.18   423.9  835.78   443.3  849.23     453  850.85
   462.8  851.97   482.6  851.01   532.1  852.38     542   854.6   581.6  874.21
   611.2  880.72     730  891.12   799.2  904.08   809.1  908.12   838.8  911.46
#Mann= 3 , 0 , 0
       0      .1       0   380.8    .045       0   395.8      .1       0
Bank Sta=380.8,395.8
XS Rating Curve= 0 ,0
Exp/Cntr=0.3,0.1

Type RM Length L Ch R = 1 ,2840.8  ,308.3,326.7,345
XS GIS Cut Line= 4
     1827828.134      423115.508     1827586.814      423004.396
       1827307.3      422879.396     1827034.731      422738.771
#Sta/Elev= 30
       0  923.82    19.7  919.29    49.2  909.27    88.6  889.53   137.8  868.54
   206.6   851.7   216.5  847.77   226.3   846.6   374.3  849.67   384.2  847.54
     404  839.23   433.6  831.68   443.5  831.51   453.3  831.51   473.1  832.82
     483  837.25   492.8  846.89   502.7  863.91   512.6  875.84   522.5  883.98
   532.4  887.66   611.4  894.79   660.9   889.2     750   890.9   759.8  892.93
   789.5   914.8   809.3  926.98   819.2  929.53   848.9  930.79   878.6  935.56
#Mann= 3 , 0 , 0
       0     .08       0   433.6    .045       0   453.3      .1       0
Bank Sta=433.6,453.3
XS Rating Curve= 0 ,0
Exp/Cntr=0.3,0.1

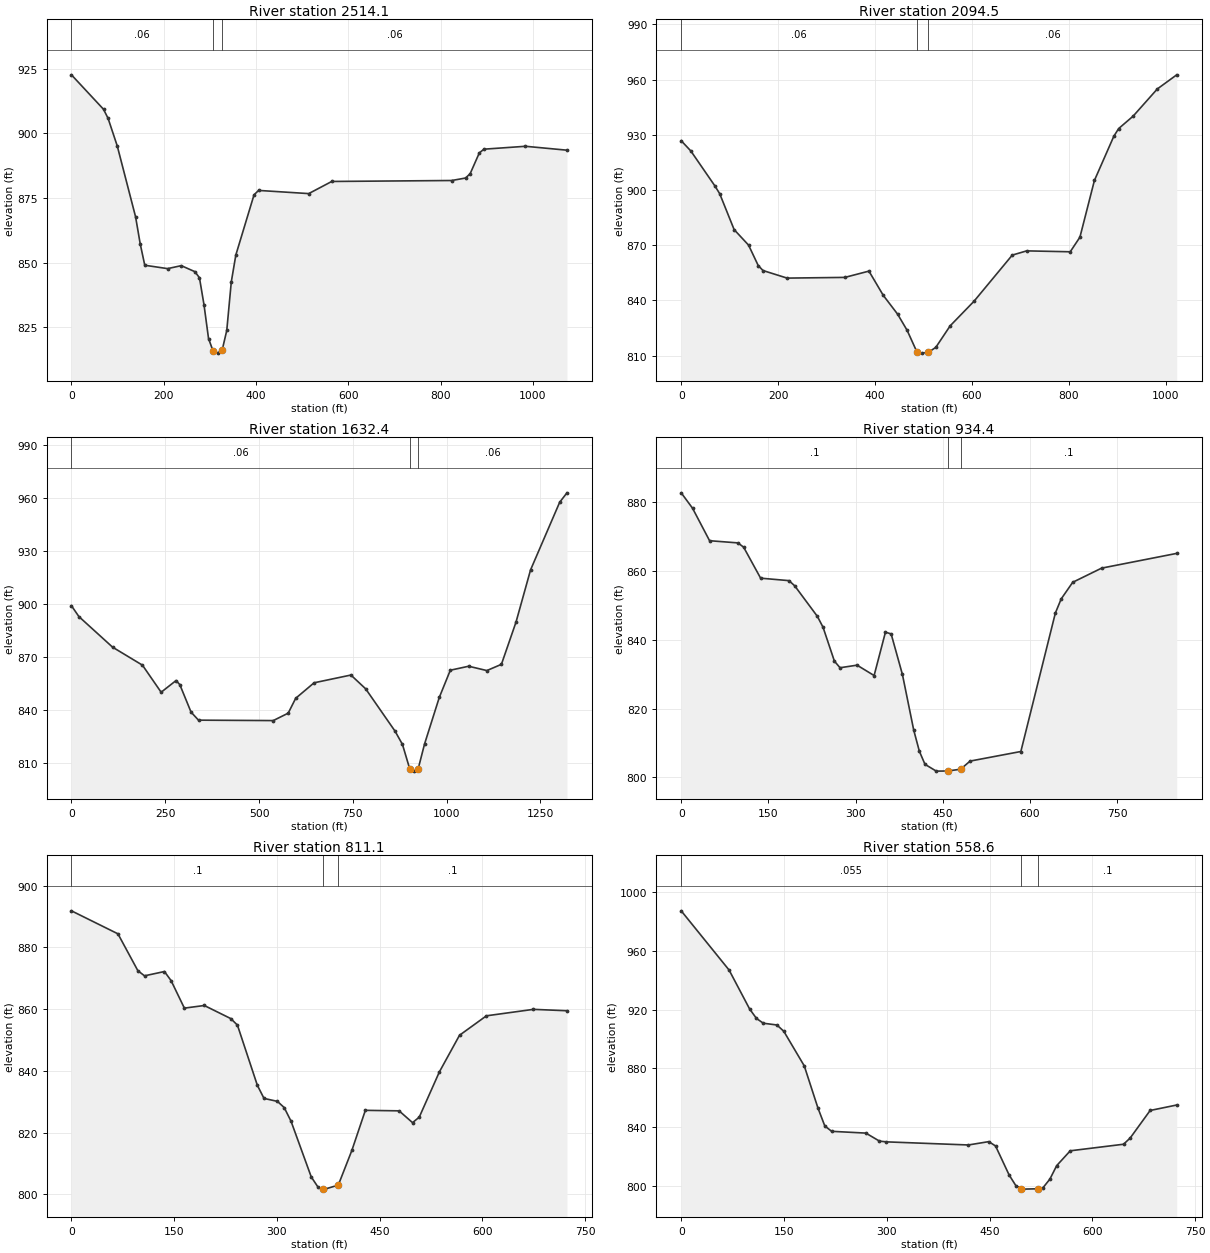
Type RM Length L Ch R = 1 ,2514.1  ,408.7,419.6,430.6
XS GIS Cut Line= 4
     1827830.217      423105.091     1827765.113      422928.008
     1827658.342      422631.133     1827500.356      422083.824
#Sta/Elev= 30
       0  922.68    69.5  909.34    79.4  905.83    99.3  895.12     139  867.69
     149  857.26   158.9  848.95   208.4  847.64     238  848.79   267.5  846.46
   277.4  844.11   287.3   833.6   297.1  820.56     307  815.69   316.8  814.92
   326.7  816.12   336.6  823.72   346.4   842.5   356.3  852.95   395.7  876.23
   405.6  877.92   514.2  876.69   564.1  881.39     824  881.76     854  882.72
     864  884.39   883.9  892.46   893.9  893.89   983.9  895.01  1073.8   893.5
#Mann= 3 , 0 , 0
       0     .06       0     307    .045       0   326.7     .06       0
Bank Sta=307,326.7
XS Rating Curve= 0 ,0
Exp/Cntr=0.3,0.1

Type RM Length L Ch R = 1 ,2094.5  ,469.7,462.1,453.9
XS GIS Cut Line= 4
     1828042.215      423295.884     1828112.712      422904.974
     1828151.985      422601.966      1828195.86      422285.467
#Sta/Elev= 30
       0   926.8    19.9  921.21    69.5  902.23    79.4  898.01   109.2  878.48
     139  870.04   158.9  858.94   168.8  856.23   218.5  852.12   337.6   852.5
   387.3  855.92   416.9  842.73   446.5  832.51   466.2  823.69   485.9   812.2
   495.8  811.34     510  811.74   525.4  814.52   554.9  826.18   604.2  839.57
     683  864.62   712.7  866.92   802.6  866.43   822.6  874.37   852.5   905.2
   892.5   929.2   902.5   933.4   932.4  940.16   982.3  954.94  1022.3  962.61
#Mann= 3 , 0 , 0
       0     .06       0   485.9    .045       0     510     .06       0
Bank Sta=485.9,510
XS Rating Curve= 0 ,0
Exp/Cntr=0.3,0.1

Type RM Length L Ch R = 1 ,1632.4  ,664.6,698,731.6
XS GIS Cut Line= 4
     1828498.103      423525.716     1828560.444      422931.301
      1828459.04      422501.411     1828413.468      422223.633
#Sta/Elev= 30
       0  899.01    19.9  892.86   109.6  875.58   189.3  865.39   239.1  850.09
   278.9   856.7   288.9  854.38   318.8  838.86   338.7   834.3   537.9  834.06
   577.8  838.26   597.7  846.65   646.8  855.43   744.9  859.81   784.2  852.03
   862.7  828.04   882.3  820.59     902  806.54   911.8  805.48   924.4  806.91
   941.2  820.82   980.5  847.16  1009.9  862.54  1058.8  864.79  1107.3  862.34
  1146.1  865.87    1185  889.74  1223.8  919.28  1301.4  957.52  1320.8  962.84
#Mann= 3 , 0 , 0
       0     .06       0     902    .045       0   924.4     .06       0
Bank Sta=902,924.4
XS Rating Curve= 0 ,0
Exp/Cntr=0.3,0.1

Type RM Length L Ch R = 1 ,934.4   ,126.8,123.3,120.4
XS GIS Cut Line= 4
     1828609.923      423428.697      1828776.59      423108.384
      1828995.34      423028.523     1829151.315      422822.591
#Sta/Elev= 30
       0  882.79    19.5  878.31    48.8  868.86    97.6  868.22   107.4  866.97
   136.6  857.96   185.4  857.24   195.2  855.74   234.2  846.85     244  843.67
   263.5  833.82   273.2   831.9   302.5  832.65   331.8  829.63   351.3  842.25
   361.1  841.74   380.5  829.94   399.9  813.78   409.6  807.62   419.3   803.8
   438.7  801.82   458.1  801.86   480.5  802.37   496.9  804.74   584.2  807.53
   643.6  847.84   653.6  851.93   673.4  856.76   723.1  860.88   852.3  865.17
#Mann= 3 , 0 , 0
       0      .1       0   458.1    .045       0   480.5      .1       0
Bank Sta=458.1,480.5
XS Rating Curve= 0 ,0
Exp/Cntr=0.3,0.1

Type RM Length L Ch R = 1 ,811.1   ,275.8,252.6,228.7
XS GIS Cut Line= 4
     1828729.715      423464.287     1828875.548      423212.551
     1829021.381      423129.217     1829183.867      422920.248
#Sta/Elev= 30
       0   891.8    67.9  884.35      97  872.41   106.7  870.75   135.8  872.14
   145.5   869.2   164.9  860.29     194  861.14   232.7   856.9   242.4  854.78
   271.5  835.28   281.2  831.05   300.8  830.09   310.7  828.08   320.6   823.7
   350.2  805.62   360.1  802.31     368   801.8     370  801.67   389.7  802.98
   409.5  814.21   429.2  827.19   478.5  827.02   498.1   823.2   507.9  824.98
   537.3  839.64   566.7   851.5     606   857.8   674.6  859.89   723.6  859.44
#Mann= 3 , 0 , 0
       0      .1       0     368    .045       0   389.7      .1       0
Bank Sta=368,389.7
XS Rating Curve= 0 ,0
Exp/Cntr=0.3,0.1

Type RM Length L Ch R = 1 ,558.6   ,269.5,259.1,248.8
XS GIS Cut Line= 4
      1829174.81      423698.553     1829191.086      423279.717
     1829197.597      423121.296     1829191.086      422975.897
#Sta/Elev= 30
       0  987.05    69.9  946.83    99.8  920.46   109.8  914.01   119.8  910.74
   139.7  909.54   149.7  905.29   179.6  881.78   199.6  853.14   209.6  840.97
   219.6  837.35   269.5  836.14   289.4  830.69   299.4  830.19   419.2  828.08
   448.9  830.35   458.8  827.39   478.6   807.7   488.5   800.4  496.61798.5159
   498.4   798.1  520.47798.3406   528.2  799.16   538.1  804.91     548  814.04
   567.8  824.12   645.6  828.58   655.3  832.82   684.4   851.5   723.2  855.21
#Mann= 3 , 0 , 0
       0    .055       0  496.61    .045       0  520.47      .1       0
Bank Sta=496.61,520.47
XS Rating Curve= 0 ,0
Exp/Cntr=0.3,0.1

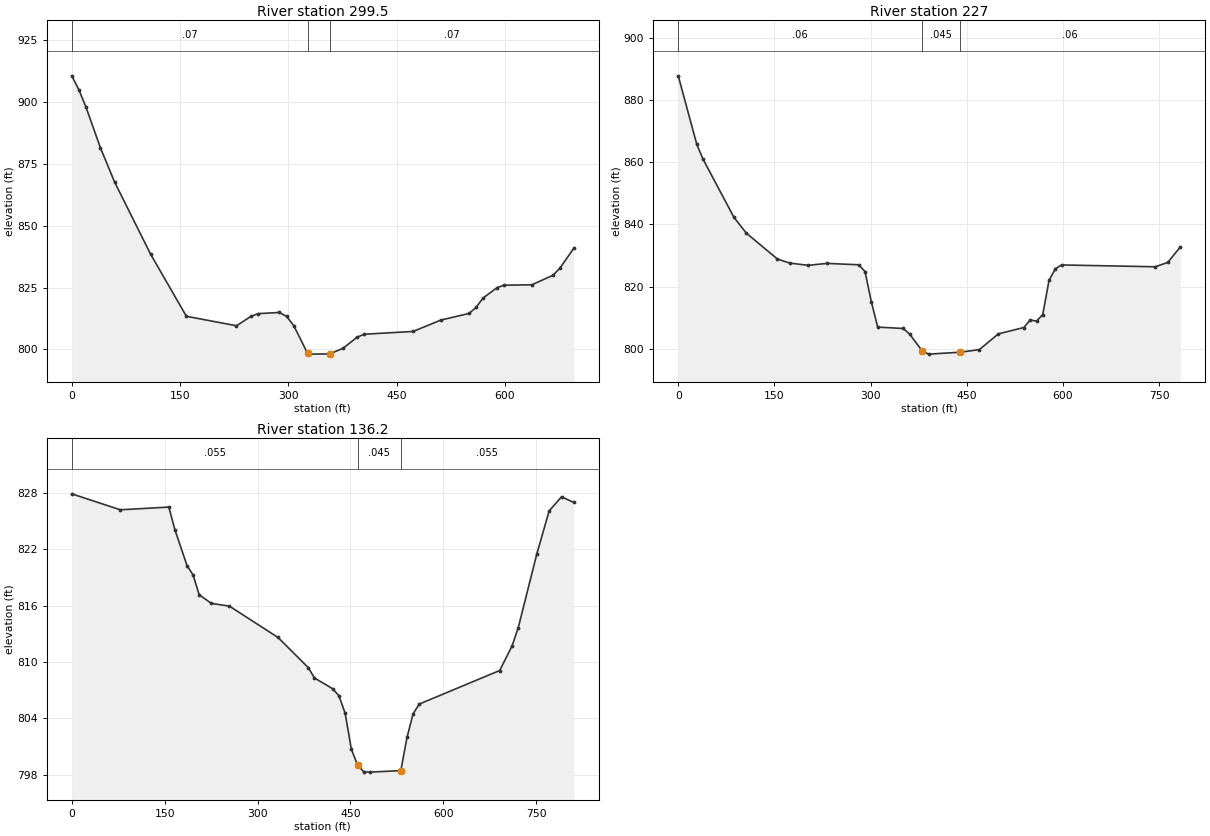
Type RM Length L Ch R = 1 ,299.5   ,72.7,72.4,71.8
XS GIS Cut Line= 4
     1829553.138       423476.91     1829460.907       423173.09
     1829406.653      423048.307     1829262.339       422854.08
#Sta/Elev= 30
       0  910.65     9.9  904.99    19.8  897.91    39.7  881.54    59.5  867.59
   109.1  838.59   158.8   813.4   228.2  809.58     248  813.32     258  814.47
   287.7  814.95   297.7  813.34   307.6   809.6  326.78 798.368   327.2   798.1
  357.62798.1968   375.8  800.46   395.3  804.94     405  806.14   472.9  807.27
   511.6   811.9   550.4  814.54     560  816.96   569.7  820.75   589.1  824.97
   598.8  825.97   637.5  826.15   666.5  829.97   676.2  832.84   695.6  840.95
#Mann= 3 , 0 , 0
       0     .07       0  326.78    .045       0  357.62     .07       0
Bank Sta=326.78,357.62
XS Rating Curve= 0 ,0
Exp/Cntr=0.3,0.1

Type RM Length L Ch R = 1 ,227     ,94.9,90.8,86.8
XS GIS Cut Line= 4
     1829665.551      423478.646     1829581.519       423273.06
     1829431.176      422971.701     1829295.759      422792.882
#Sta/Elev= 30
       0  887.84      29  865.75    38.6  861.05    86.9  842.31   106.2  837.22
   154.5  828.92   173.8  827.58   202.8  826.86     232  827.48   281.5  827.03
   291.4  824.86   301.3  815.03   311.2  806.98   350.9  806.53   360.8  804.76
   380.6  799.32   390.5  798.28     440   798.9   469.7  799.73   499.4  804.81
   539.1  806.84     549  809.28   558.9  808.91   568.6     811   578.4  822.01
   588.1   825.7   597.9  826.98   744.2  826.39   763.7   827.8   783.2  832.78
#Mann= 3 , 0 , 0
       0     .06       0   380.6    .045       0     440     .06       0
Bank Sta=380.6,440
XS Rating Curve= 0 ,0
Exp/Cntr=0.3,0.1

Type RM Length L Ch R = 1 ,136.2   ,135.2,136.2,137.2
XS GIS Cut Line= 4
     1829740.204      423451.736     1829579.613      423083.681
     1829479.787      422934.375     1829346.106      422747.743
#Sta/Elev= 30
       0  827.92    78.4  826.22   156.7  826.51   166.5   824.1   186.1  820.28
   195.9  819.28   205.7  817.18   225.3  816.26   254.6  815.96     333  812.63
     382  809.41   391.8  808.32   421.5  807.16   431.5  806.41   441.5  804.54
   451.4  800.74   461.4  799.06   471.4  798.33   481.4  798.29   531.3  798.45
   541.3  801.98   551.2  804.51   561.2  805.54     691  809.11   710.9  811.72
   720.9  813.66   750.8  821.49   770.8   826.1   790.8   827.6   810.7     827
#Mann= 3 , 0 , 0
       0    .055       0   461.4    .045       0   531.3    .055       0
Bank Sta=461.4,531.3
XS Rating Curve= 0 ,0
Exp/Cntr=0.3,0.1

Chan Stop Cuts=-1
Use User Specified Reach Order=0
Composite Channel Slope=5